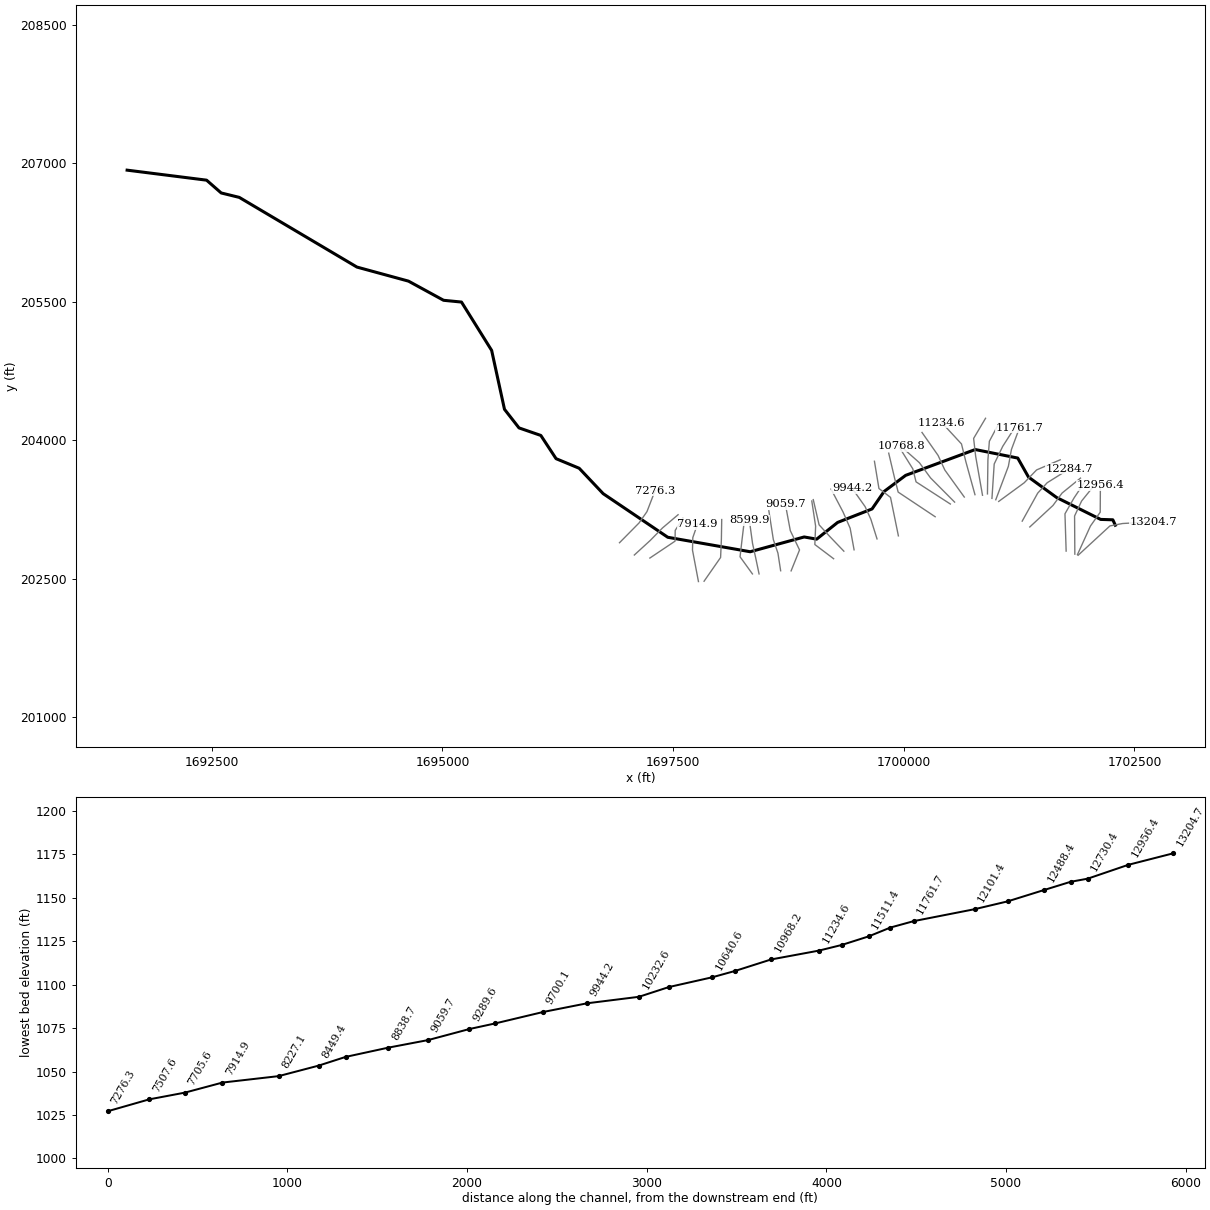
--- sprngfrk.prj (project) ---

Proj Title=sprngfrk
Current Plan=p01
Default Exp/Contr=0,0
English Units
Geom File=g01
Flow File=f01
Plan File=p01
BEGIN DESCRIPTION:
END DESCRIPTION:
DSS Export Rating Curves= 0
DSS Export Rating Curve Sorted= 0
DSS Export Volume Flow Curves= 0
DXF OffsetX= 0
DXF OffsetY= 0
DXF ScaleX= 0
DXF ScaleY= 0

--- sprngfrk.p01 (plan) ---

Plan Title=Floodplain
Program Version=4.00
Geom File=g01
Flow File=f01
K Sum by GR=0
Std Step Tol=0.01
Critical Tol=0.01
Num of Std Step Trials=20
Max Error Tol=0.3
Flow Tol Ratio=0.001
Split Flow NTrial=30
Split Flow Tol=0.02
Split Flow Ratio=0.02
Log Output Level=0
Friction Slope Method=1
Unsteady Friction Slope Method=2
Unsteady Bridges Friction Slope Method=1
Global Log Level=0
CheckData=False
Run HTab=0
Run UNet=0
Run PostProcess=0
UNET Theta=0
UNET Theta Warmup=0
UNET ZTol=0
UNET ZSATol=0
UNET MxIter=0
UNET MaxInSteps=0
UNET DtIC=0
UNET DtMin=0
UNET MaxCRTS=0
UNET WFStab=0
UNET SFStab=0
UNET WFX=0
UNET SFX=0
UNET DSS MLevel=0
UNET DZMax Abort=0
UNET Convert EG Bridges=0
UNET Use Existing IB Tables=0
UNET Froude Limit=0
UNET Froude Power=0
Write IC File=0
Echo Input=False
Echo Output=False
Write Detailed=0

--- sprngfrk.f01 (steady flow) ---

Flow Title=NFF Regression Equation
Program Version=4.00
Number of Profiles= 1
Profile Names=P100yr
River Rch & RM=sprngfrk,Main            ,13204.7
     306
River Rch & RM=sprngfrk,Main            ,12730.4
     363
River Rch & RM=sprngfrk,Main            ,12488.4
     374
River Rch & RM=sprngfrk,Main            ,11234.6
     412
River Rch & RM=sprngfrk,Main            ,9944.2
     445
River Rch & RM=sprngfrk,Main            ,8838.7
     481
River Rch & RM=sprngfrk,Main            ,7914.9
     517
River Rch & RM=sprngfrk,Main            ,7705.6
     573
River Rch & RM=sprngfrk,Main            ,4391.3
     629
River Rch & RM=sprngfrk,Main            ,4095.2
     962
River Rch & RM=sprngfrk,Main            ,287.3
    1017
Boundary for River Rch & Prof#=sprngfrk,Main            , 1
Up Type= 0
Dn Type= 3
Dn Slope=0.026
DSS Import GetInterval= 0
DSS Import GetPeak= 0
DSS Import FillOption= 0

--- sprngfrk.g01 (geometry) ---

Geom Title=USGS 10m DEM
Program Version=4.00

River Reach=sprngfrk        ,Main
Reach XY= 30
     1702293.351      203077.662     1702266.034      203136.108
      1702134.03      203140.286     1701657.577      203377.167
     1701352.293      203598.924     1701235.614       203804.89
     1700774.798      203897.138     1700020.767      203617.508
     1699786.861      203442.695     1699656.668       203253.72
     1699283.455      203107.667     1699056.388      202926.673
     1698920.738      202950.132     1698335.779      202790.149
     1697442.623      202946.874     1696742.258      203419.233
     1696482.363      203694.428     1696231.818       203798.24
     1696066.703       204049.77     1695830.129      204131.468
     1695672.677      204333.171     1695533.558      204970.917
     1695206.823      205494.524     1695012.646      205513.616
     1694632.368      205721.161     1694073.607      205873.363
     1692798.398      206628.205     1692602.317      206676.197
     1692443.944      206814.687     1691582.641      206923.219

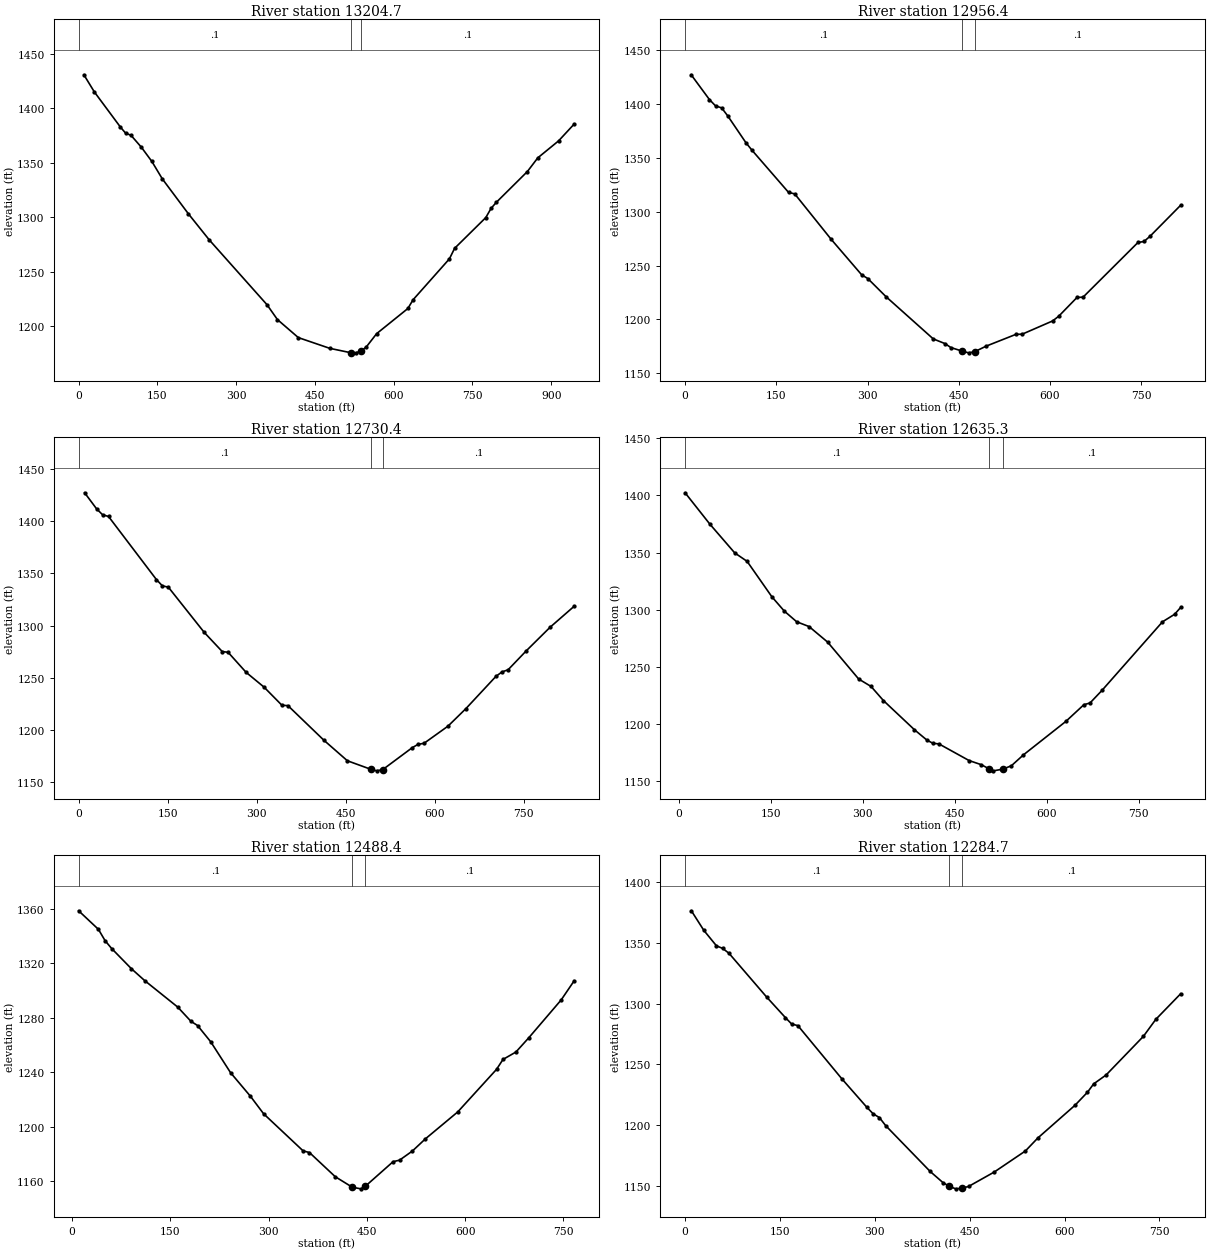
Type RM Length L Ch R = 1 ,13204.7 ,232.4,248.3,264.2
XS GIS Cut Line= 4
     1701890.586      202752.461     1702234.907      203069.813
     1702371.341      203095.865     1702707.283      203115.176
#Sta/Elev= 30
      10 1430.74    29.9 1415.03    79.7 1382.67    89.7 1377.05    99.6 1375.28
   119.6 1364.18   139.5 1351.18   159.4 1335.19   209.2 1303.06   249.1 1279.04
   358.7 1219.77   378.6 1206.12   418.4 1189.58   478.2 1179.74   517.8 1175.75
   527.8  1175.6   537.8 1177.25   547.6 1180.87   567.5 1193.19     627 1216.29
   636.9 1224.29   706.1 1261.83     716 1271.49   775.4 1299.71   785.3 1308.05
   795.2 1313.58   854.6 1341.96   874.4 1354.51     914 1370.08   943.7 1385.52
#Mann= 3 , 0 , 0
       0      .1       0   517.8    .045       0   537.8      .1       0
Bank Sta=517.8,537.8
XS Rating Curve= 0 ,0
Exp/Cntr=0.3,0.1

Type RM Length L Ch R = 1 ,12956.4 ,222.4,226,229.6
XS GIS Cut Line= 4
     1701882.739      202758.666     1702023.515      203068.556
     1702129.554      203218.473     1702131.382      203509.166
#Sta/Elev= 30
      10  1427.1      40 1404.11    50.1 1398.21    60.1 1396.37    70.1 1388.95
   100.1 1363.97   110.1    1357   170.2 1317.88   180.2 1316.58   240.3 1274.29
   290.3 1241.44   300.3 1238.02   330.4 1221.11     408 1181.96   427.3  1177.6
     437 1173.92     456 1170.56     466 1169.03     476 1170.06     495 1175.26
     544 1186.21   554.1 1186.32   604.2 1198.63   614.2 1202.98   644.3 1220.43
   654.3 1220.72   744.5 1271.44   754.5 1272.39   764.6 1277.35   814.7 1305.99
#Mann= 3 , 0 , 0
       0      .1       0     456    .045       0     476      .1       0
Bank Sta=456,476
XS Rating Curve= 0 ,0
Exp/Cntr=0.3,0.1

Type RM Length L Ch R = 1 ,12730.4 ,96.7,95.1,93.5
XS GIS Cut Line= 4
     1701854.401      202764.151     1701851.659      203177.337
     1701927.531      203339.138     1702080.191      203528.362
#Sta/Elev= 30
    10.1 1427.27    30.2 1411.94    40.3 1406.27    50.4 1404.57     131 1344.23
   141.1 1338.17   151.2 1336.89   211.6 1293.63   241.9  1275.3   251.9 1274.52
   282.2 1255.36   312.4 1241.21   342.6 1223.81   352.7 1223.48   413.2 1190.39
   452.9 1170.68   492.5 1162.51   502.5 1161.05   512.5 1162.26   562.1 1183.21
     572 1186.42     582 1187.42   622.3  1203.8   652.7  1220.7   703.3 1251.57
   713.5  1255.8   723.6 1257.78     754  1275.8   794.5 1298.57     835 1318.62
#Mann= 3 , 0 , 0
       0      .1       0   492.5    .045       0   512.5      .1       0
Bank Sta=492.5,512.5
XS Rating Curve= 0 ,0
Exp/Cntr=0.3,0.1

Type RM Length L Ch R = 1 ,12635.3 ,149.2,146.9,144.6
XS GIS Cut Line= 4
     1701760.246      202797.059     1701747.448      203201.104
      1701845.26      203372.046     1701965.925       203552.13
#Sta/Elev= 30
    10.1 1402.19    50.5 1374.78      91 1349.67   111.2 1342.28   151.6 1311.31
   171.8 1298.85     192  1289.5   212.2 1285.31   242.5 1271.72   293.1 1239.47
   313.3 1232.97   333.5 1220.62     384 1195.17   404.2 1186.18   414.1  1183.3
   423.9  1182.8   473.2 1168.21   492.9 1164.65  505.83 1160.98   512.6 1159.25
  528.11 1160.72   542.1 1163.71   561.8 1173.24   630.8 1202.41   660.3 1217.05
   670.2 1218.51   689.9  1229.6   788.4 1289.45   808.1    1296     818    1302
#Mann= 3 , 0 , 0
    10.1      .1       0  505.83    .045       0  528.11      .1       0
Bank Sta=505.83,528.11
XS Rating Curve= 0 ,0
Exp/Cntr=0.3,0.1

Type RM Length L Ch R = 1 ,12488.4 ,205.8,203.7,201.6
XS GIS Cut Line= 4
     1701366.256        203058.5     1701617.642      203291.603
     1701716.368       203425.98     1701915.648      203587.781
#Sta/Elev= 30
    10.1 1358.48    40.3 1344.87    50.4 1336.61    60.5  1330.8    90.7 1315.96
   110.9 1307.28   161.3 1287.86   181.5 1277.41   191.6 1274.31   211.7 1262.38
     242 1239.71   272.2 1222.49   292.4  1209.6   352.6 1182.42   362.4 1181.15
   401.7 1163.45  427.76 1155.72   440.9 1154.55  447.69 1156.49     490 1174.48
   499.8 1175.58   519.4 1182.27   539.2 1191.18   588.6 1210.95   647.8 1242.17
   657.7 1249.46   677.4 1254.89   697.2 1265.43   746.5 1293.12   766.3 1307.14
#Mann= 3 , 0 , 0
    10.1      .1       0  427.76    .045       0  447.69      .1       0
Bank Sta=427.76,447.69
XS Rating Curve= 0 ,0
Exp/Cntr=0.3,0.1

Type RM Length L Ch R = 1 ,12284.7 ,183.9,183.3,182.8
XS GIS Cut Line= 4
     1701283.985      203121.727     1701452.185      203425.218
     1701554.567      203537.351     1701795.897      203688.487
#Sta/Elev= 30
     9.9 1376.12    29.7    1360    49.6 1347.36    59.5 1345.22    69.4 1341.25
   128.9 1305.37   158.6 1288.48   168.5 1283.22   178.4 1281.87   247.8 1238.29
   287.5 1214.84   297.4 1209.54   307.3 1206.41   317.2 1199.83   387.5 1162.26
   407.7 1153.13     418 1149.98     428 1147.98     438 1148.55   448.2 1149.92
   488.7 1161.72   538.1 1179.04   557.7 1189.66   616.7 1216.61   636.3 1227.25
   646.1 1234.11   665.7 1241.38   724.7 1273.09   744.3 1287.01   783.6 1308.01
#Mann= 3 , 0 , 0
       0      .1       0     418    .045       0     438      .1       0
Bank Sta=418,438
XS Rating Curve= 0 ,0
Exp/Cntr=0.3,0.1

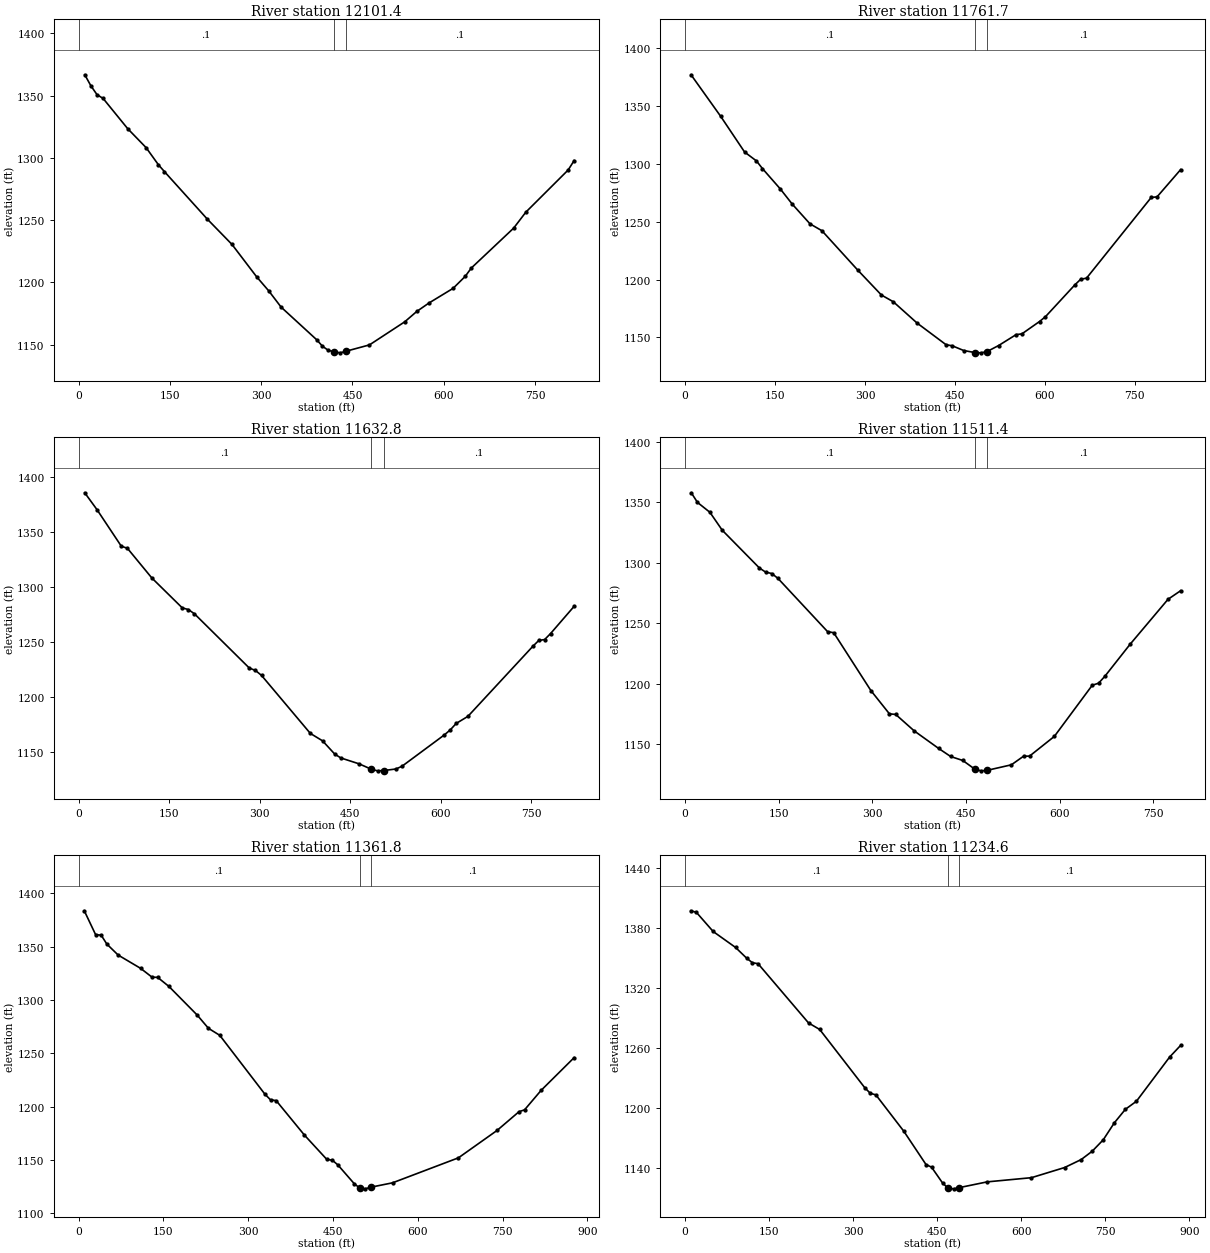
Type RM Length L Ch R = 1 ,12101.4 ,327.6,339.7,351.8
XS GIS Cut Line= 4
     1701029.248      203335.024     1701305.924      203537.351
     1701439.996      203676.299     1701695.952      203785.994
#Sta/Elev= 30
    10.1 1366.69    20.2 1357.79    30.2 1350.74    40.3 1347.66    80.6 1323.45
   110.9  1308.2   131.1 1294.47   141.1  1288.9   211.7  1250.7     252 1230.51
   292.4 1204.59   312.5 1193.17   332.7 1180.21     391 1154.08   400.7  1148.8
   410.3 1145.49   419.6  1144.4   429.7 1143.49   439.6 1144.81   477.9 1149.86
   535.8 1168.37   555.7 1176.74   575.6 1183.46   615.4 1195.28   635.3 1204.89
   645.2 1211.53   714.9 1243.62   734.8 1256.37   804.4 1290.26   814.3 1297.86
#Mann= 3 , 0 , 0
       0      .1       0   419.6    .045       0   439.6      .1       0
Bank Sta=419.6,439.6
XS Rating Curve= 0 ,0
Exp/Cntr=0.3,0.1

Type RM Length L Ch R = 1 ,11761.7 ,134.1,128.9,123.6
XS GIS Cut Line= 4
     1700997.558      203353.307     1701134.068      203715.302
     1701166.976      203896.909     1701255.952      204135.801
#Sta/Elev= 30
     9.9 1377.14    59.5 1341.07    99.2 1310.33     119 1302.61     129 1295.99
   158.7 1278.43   178.6 1265.31   208.3 1248.19   228.2 1242.23   287.7  1208.3
   327.4 1186.61   347.2  1180.8   386.9 1162.35   435.4 1143.55   445.2 1142.77
   464.6 1138.61   483.7  1136.8   493.7  1136.6   503.7 1137.74   522.9 1142.94
     552 1152.35   561.7 1153.01   591.1 1163.71   600.9 1167.83   649.9 1195.34
   659.7 1200.24   669.5 1201.23   777.3 1270.99   787.1 1271.55   826.4  1295.1
#Mann= 3 , 0 , 0
       0      .1       0   483.7    .045       0   503.7      .1       0
Bank Sta=483.7,503.7
XS Rating Curve= 0 ,0
Exp/Cntr=0.3,0.1

Type RM Length L Ch R = 1 ,11632.8 ,113.9,121.4,129
XS GIS Cut Line= 4
     1700956.117      203367.933     1700980.494      203740.897
     1701073.126      203932.255     1701199.885      204129.707
#Sta/Elev= 30
    10.1 1385.34    30.3 1370.13    70.7 1336.84    80.8 1334.96   121.2 1308.06
   171.7 1280.86   181.8 1279.35   191.9 1275.47   282.8 1226.23   292.9 1224.08
     303 1219.56   383.9  1166.9   404.1 1160.17   424.4 1148.09   434.5 1144.62
   464.9 1139.24   485.2 1134.33   495.2 1132.93   505.2 1133.19   525.6  1134.6
   535.7 1137.07   605.9 1165.54   615.7 1170.08   625.5 1175.95     645  1182.4
   752.6 1246.03   762.3 1251.25   772.1 1252.13   781.9 1257.55     821 1282.31
#Mann= 3 , 0 , 0
       0      .1       0   485.2    .045       0   505.2      .1       0
Bank Sta=485.2,505.2
XS Rating Curve= 0 ,0
Exp/Cntr=0.3,0.1

Type RM Length L Ch R = 1 ,11511.4 ,145.8,149.6,153.5
XS GIS Cut Line= 4
     1700907.364      203416.686     1700912.239      203783.556
     1700928.084      203987.102     1701032.904      204183.336
#Sta/Elev= 30
     9.9 1357.75    19.8  1349.8    39.7 1341.62    59.5 1326.78     119 1295.56
   128.9 1292.17   138.8 1290.99   148.7 1286.96   228.1 1242.97     238 1242.02
   297.5 1194.21   327.2 1174.95   337.2 1174.48   366.9 1160.85   405.8 1146.43
   425.2 1139.69   444.7 1136.39   463.8 1129.26   473.8 1127.83   483.8 1128.26
   522.5 1132.82   541.9  1139.9   551.6 1140.02   591.3 1156.32     652 1198.62
   662.1 1200.28   672.2 1206.04   712.6 1232.51   773.3 1269.68   793.5 1276.77
#Mann= 3 , 0 , 0
       0      .1       0   463.8    .045       0   483.8      .1       0
Bank Sta=463.8,483.8
XS Rating Curve= 0 ,0
Exp/Cntr=0.3,0.1

Type RM Length L Ch R = 1 ,11361.8 ,124.6,127.2,129.8
XS GIS Cut Line= 4
     1700853.735       203402.06     1700779.386      203824.997
     1700757.447      204017.574     1700886.643      204235.746
#Sta/Elev= 30
      10 1383.68      30 1361.34    39.9 1360.78    49.9 1352.47    69.9 1342.16
   109.9 1329.61   129.8 1321.43   139.8 1321.23   159.8 1312.71   209.7 1285.92
   229.7 1273.44   249.7 1266.88   329.6 1211.68   339.5 1206.39   349.5 1205.66
   399.5 1173.32   439.1 1150.52   448.8 1149.76   458.5 1145.44   487.6 1127.75
     497  1123.8     507  1122.9     517 1124.44   555.4 1128.54     672 1151.98
   740.3 1177.64   779.3  1195.3     789 1196.98   818.3 1215.25   876.8 1245.99
#Mann= 3 , 0 , 0
       0      .1       0     497    .045       0     517      .1       0
Bank Sta=497,517
XS Rating Curve= 0 ,0
Exp/Cntr=0.3,0.1

Type RM Length L Ch R = 1 ,11234.6 ,262.5,266.4,270.2
XS GIS Cut Line= 4
     1700772.073      203408.154     1700673.347      203765.274
     1700625.812       203957.85     1700411.297       204189.43
#Sta/Elev= 30
      10 1397.59      20 1396.12    50.1 1376.88    90.1 1360.92   110.2 1350.04
   120.2 1345.65   130.2 1344.71   220.3 1285.49   240.3 1278.92   320.4 1220.93
   330.5 1215.14   340.5 1213.59   390.4 1177.21     430 1143.94   439.9 1141.31
   459.8 1125.29   469.6  1120.2   479.6 1119.64   489.6 1120.88   539.1  1126.6
   618.2 1130.79   677.4 1140.94     707 1148.91   726.7 1157.25   746.4 1168.68
   766.2 1185.66   785.9 1199.16   805.6 1207.19   864.8 1251.34   884.5 1263.04
#Mann= 3 , 0 , 0
       0      .1       0   469.6    .045       0   489.6      .1       0
Bank Sta=469.6,489.6
XS Rating Curve= 0 ,0
Exp/Cntr=0.3,0.1

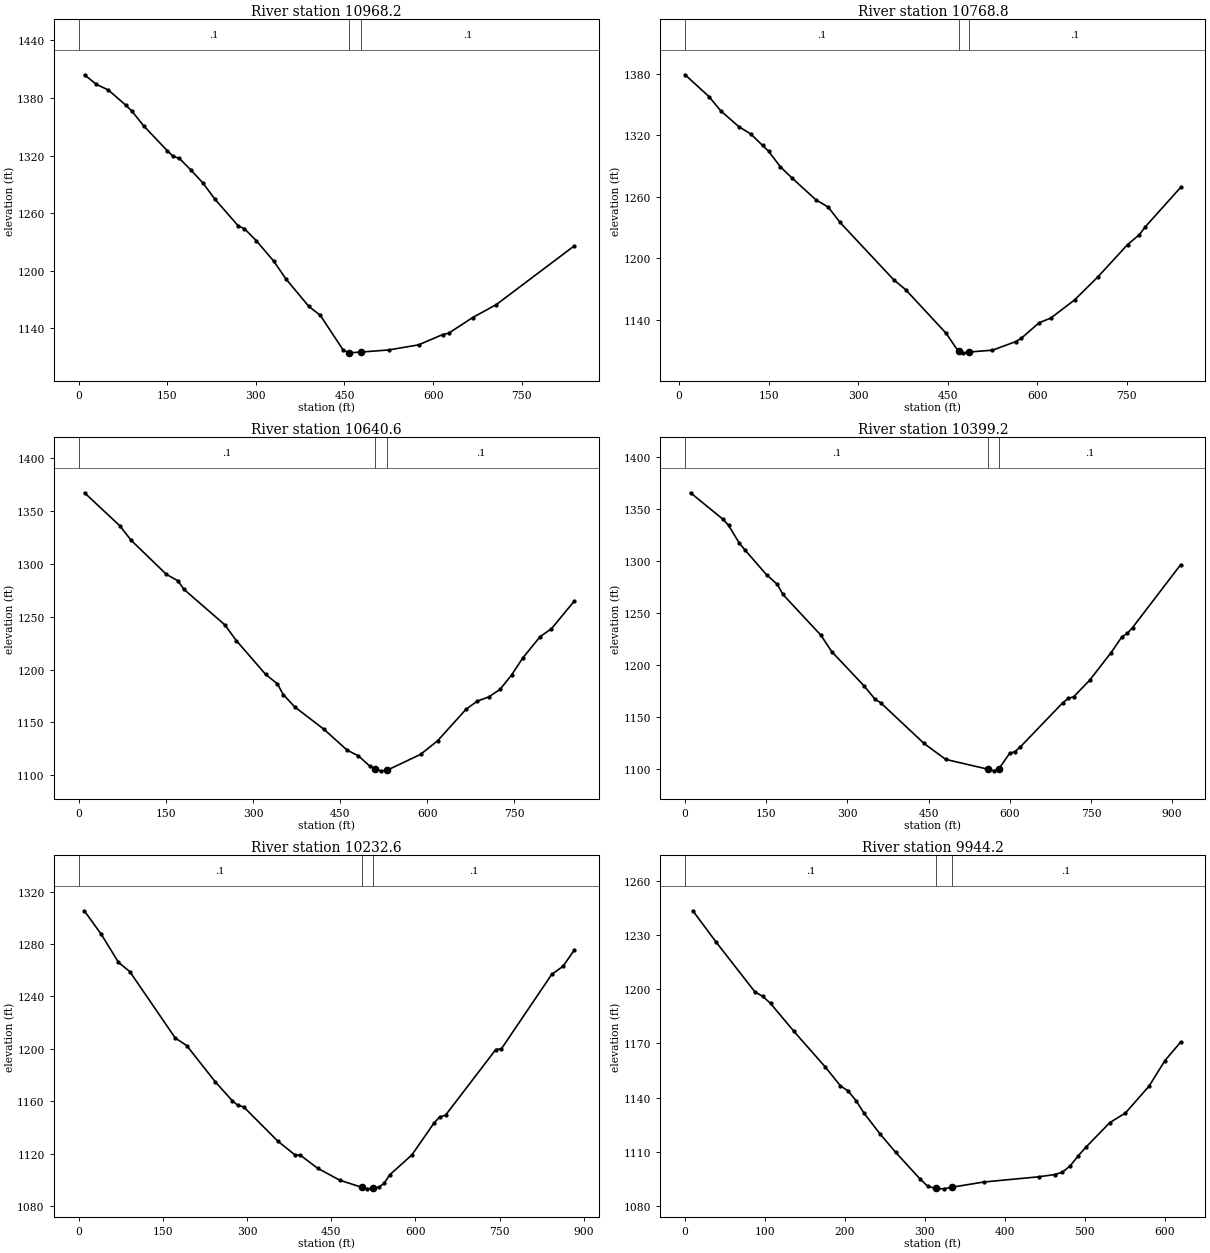
Type RM Length L Ch R = 1 ,10968.2 ,195.4,199.4,203.4
XS GIS Cut Line= 4
     1700656.283      203382.559     1700445.424       203675.08
     1700372.294      203833.529        1700198.      204082.172
#Sta/Elev= 30
      10 1404.05      30 1394.03    50.1 1388.29    80.1 1372.24    90.1 1366.27
   110.2 1350.79   150.2 1324.91   160.3 1319.01   170.3 1317.04   190.3 1304.81
   210.3 1291.44   230.4 1274.75   270.4 1246.55   280.5 1243.91   300.5 1231.46
   330.5 1209.84   350.6 1191.72   389.7 1162.86   409.1 1153.58   447.9 1117.35
   457.2 1114.63   457.5 1114.54   477.2 1115.31   525.4 1117.58   575.6 1122.87
   616.1 1133.57   626.2 1134.91   666.7 1151.18   707.2 1164.86   838.8 1225.83
#Mann= 3 , 0 , 0
       0      .1       0   457.2    .045       0   477.2      .1       0
Bank Sta=457.2,477.2
XS Rating Curve= 0 ,0
Exp/Cntr=0.3,0.1

Type RM Length L Ch R = 1 ,10768.8 ,136,128.2,120.4
XS GIS Cut Line= 4
     1700551.463      203327.711     1700290.632      203589.761
     1700169.967      203754.304     1699970.077      203931.036
#Sta/Elev= 30
      10 1379.06      50 1357.82    69.9 1343.83    99.9 1328.54   119.9 1321.38
   139.9 1310.16   149.9 1304.52   169.9 1289.22   189.9 1278.05   229.8 1256.89
   249.8 1250.11   269.8 1235.06   359.7 1179.16   379.5 1169.66   447.5 1127.03
   466.9 1110.38  469.27 1109.77   476.6 1107.96   486.6 1108.79   525.2 1110.55
   564.1 1118.88   573.8 1122.31   603.4 1137.28   623.2 1141.94   662.7 1159.49
   702.2  1182.2   751.7 1213.52   771.4 1223.12   781.3 1230.82   840.6 1269.25
#Mann= 3 , 0 , 0
      10      .1       0  469.27    .045       0   486.6      .1       0
Bank Sta=469.27,486.6
XS Rating Curve= 0 ,0
Exp/Cntr=0.3,0.1

Type RM Length L Ch R = 1 ,10640.6 ,244.6,241.5,241.6
XS GIS Cut Line= 4
     1700505.147      203306.991     1700133.402      203547.102
     1700098.055      203688.487     1699957.889      203912.754
#Sta/Elev= 30
    10.1 1366.95    70.4 1336.03    90.5 1321.98   150.9 1289.93     171 1283.78
     181 1275.81   251.4 1242.29   271.6 1227.17   321.9 1195.33     342 1186.48
     352 1176.38   372.1 1164.58   422.4 1143.41     462 1123.83   481.4 1118.48
   500.8 1108.84   510.3 1105.99   520.3 1104.28   530.3 1104.72   588.3  1119.8
   617.7 1132.67   666.6 1162.43   686.2 1170.19   705.8  1174.1   725.4 1181.33
     745 1194.83   764.6 1211.15     794 1230.96   813.6 1238.53   852.7 1264.51
#Mann= 3 , 0 , 0
       0      .1       0   510.3    .045       0   530.3      .1       0
Bank Sta=510.3,530.3
XS Rating Curve= 0 ,0
Exp/Cntr=0.3,0.1

Type RM Length L Ch R = 1 ,10399.2 ,153.1,166.6,180
XS GIS Cut Line= 4
     1700340.604      203169.262     1699939.606      203436.188
     1699900.603      203588.543     1699837.224      203857.906
#Sta/Elev= 30
      10 1365.36    70.2 1339.88    80.3 1334.09   100.4 1316.83   110.4 1310.66
   150.5 1286.71   170.6 1277.39   180.6 1267.91   250.9 1228.76     271 1212.98
   331.2 1179.86   351.2 1167.22   361.3 1164.01   441.6 1124.88   481.7 1109.61
   560.2 1100.13   570.2 1098.65   580.2 1100.86   599.7 1115.48   609.5 1117.08
   619.3 1121.52   698.3 1164.17   708.2 1168.15     718 1169.68   747.7 1185.62
   787.2 1212.09     807 1227.05   816.9 1230.45   826.8 1236.04   915.7 1296.37
#Mann= 3 , 0 , 0
       0      .1       0   560.2    .045       0   580.2      .1       0
Bank Sta=560.2,580.2
XS Rating Curve= 0 ,0
Exp/Cntr=0.3,0.1

Type RM Length L Ch R = 1 ,10232.6 ,298.3,288.4,278.4
XS GIS Cut Line= 4
     1699942.044       202962.06     1699856.725      203378.902
     1699731.185       203475.19     1699682.431      203770.149
#Sta/Elev= 30
    10.1 1305.45    40.5 1287.37    70.9 1266.11    91.2 1258.95   172.2 1208.22
   192.5 1202.47   243.1 1174.97   273.5 1160.45   283.7 1156.78   293.8 1155.71
   354.6 1129.56     385 1119.09   395.1 1118.71   425.5 1108.83     465 1099.69
   504.5 1094.17   514.5 1093.04   524.5 1093.55   534.3 1094.26   544.1  1097.2
     554 1103.69   593.7    1119   633.5 1143.59   643.5 1148.04   653.5 1149.25
   743.1 1199.48   753.1 1200.03   842.8  1256.9   862.7 1262.98   882.7 1275.28
#Mann= 3 , 0 , 0
       0      .1       0   504.5    .045       0   524.5      .1       0
Bank Sta=504.5,524.5
XS Rating Curve= 0 ,0
Exp/Cntr=0.3,0.1

Type RM Length L Ch R = 1 ,9944.2  ,244.5,244.2,243.9
XS GIS Cut Line= 4
     1699710.465      202929.151     1699643.429      203142.448
     1699581.268      203278.958     1699438.664      203480.066
#Sta/Elev= 30
     9.7 1243.67    38.9 1226.23    87.5 1198.59    97.2 1196.16   106.9 1192.24
   136.1 1176.78     175 1157.18   194.4 1146.49   204.1  1143.6   213.9 1138.28
   223.6  1131.5   243.6 1119.98   263.6 1109.53   293.6 1094.98   303.6 1090.73
   313.6  1089.5   323.6 1089.31   333.6 1090.18   373.6  1093.1   442.6    1096
   462.3 1097.22   472.2 1098.55   482.1 1102.17   491.9 1107.63   501.8 1112.53
   531.4 1126.04   551.1 1131.43   580.7 1146.41   600.4 1160.47   620.1 1170.79
#Mann= 3 , 0 , 0
       0      .1       0   313.6    .045       0   333.6      .1       0
Bank Sta=313.6,333.6
XS Rating Curve= 0 ,0
Exp/Cntr=0.3,0.1

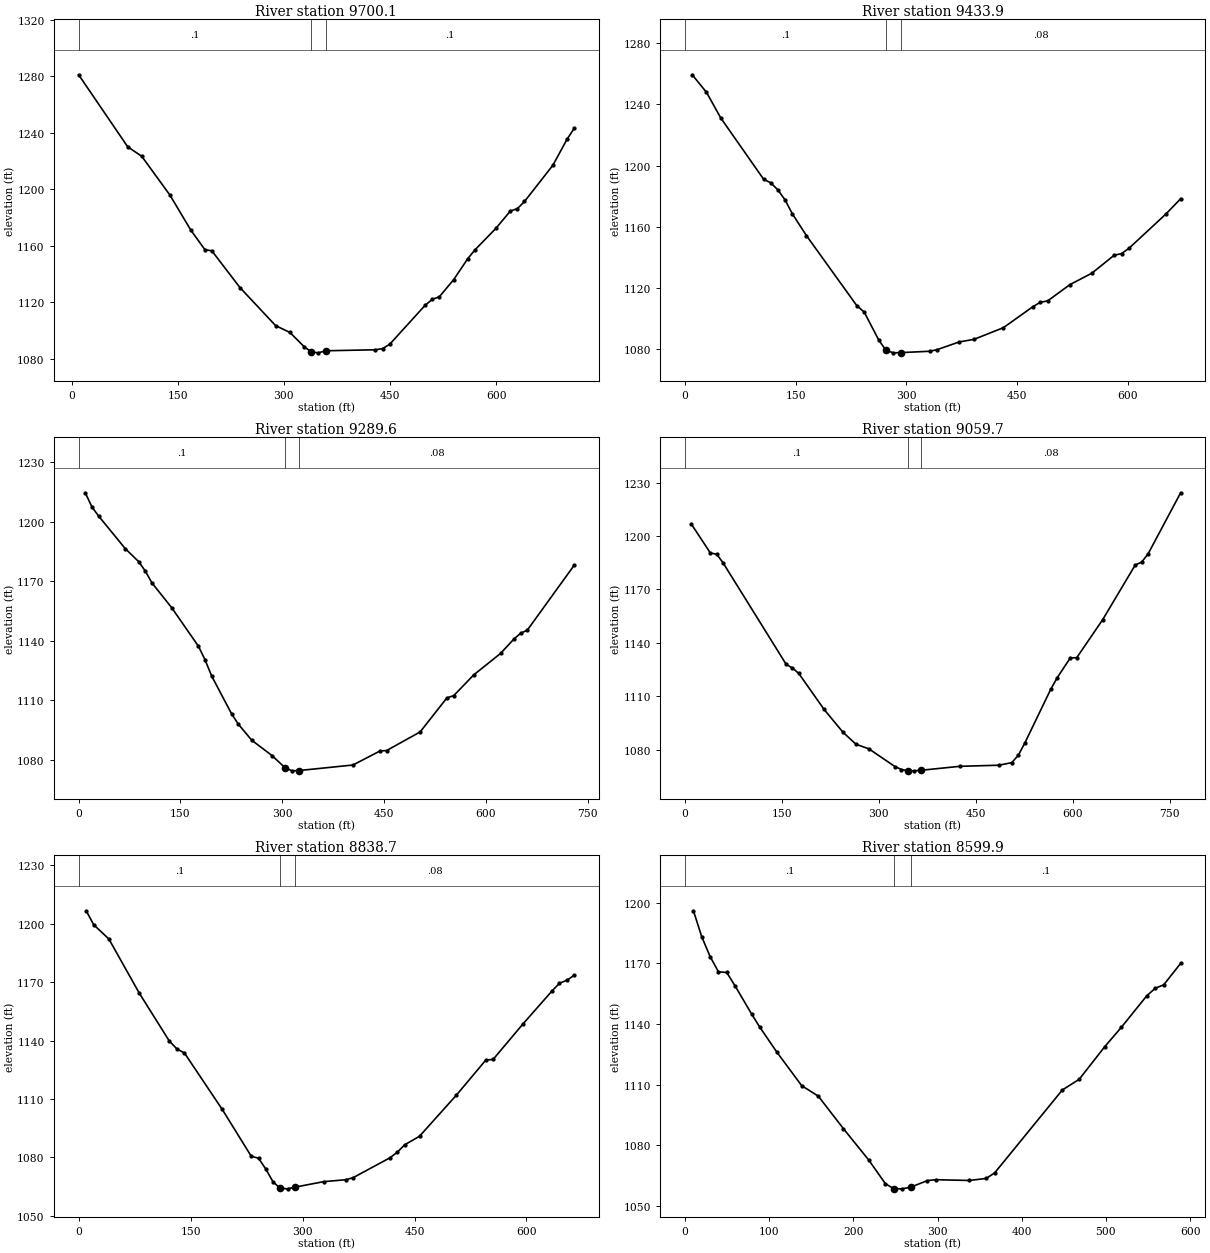
Type RM Length L Ch R = 1 ,9700.1  ,259.6,266.2,272.8
XS GIS Cut Line= 4
     1699461.822      202810.924     1699419.162      203044.941
     1699342.376      203220.453      1699211.96      203469.096
#Sta/Elev= 30
     9.9 1281.01    79.3 1230.04    99.1 1223.34   138.8 1195.99   168.5 1171.08
   188.3 1157.33   198.2 1156.45   237.9 1130.47   288.3 1103.55   308.5 1098.73
   328.6 1088.65   338.8 1084.94   348.8 1084.31   358.8 1085.77   429.4 1086.48
   439.5 1087.33   449.5 1090.36   499.6 1117.96   509.7 1122.15   519.7 1123.99
   539.8    1136   559.8 1150.92   569.8 1157.04   599.9 1172.55     620 1184.63
     630 1186.32     640 1191.38   680.1    1217   700.2 1235.49   710.2 1243.03
#Mann= 3 , 0 , 0
     9.9      .1       0   338.8    .045       0   358.8      .1       0
#XS Ineff= 2 , 0
       0                     369       0
Permanent Ineff=
       F       F
Bank Sta=338.8,358.8
XS Rating Curve= 0 ,0
Exp/Cntr=0.3,0.1

Type RM Length L Ch R = 1 ,9433.9  ,160.1,144.3,128.4
XS GIS Cut Line= 4
     1699350.907      202796.298     1699203.428      202949.871
     1699082.763      203081.506     1699019.384      203354.525
#Sta/Elev= 30
     9.7 1259.27      29 1247.82    48.4 1231.04   106.5 1191.05   116.1 1188.73
   125.8  1184.1   135.5  1177.6   145.2 1168.64   164.5 1154.28   232.8 1108.54
   242.7 1104.43   262.5 1086.15   272.4 1079.32   282.4 1077.74   292.4 1077.88
     332 1078.78   341.9 1079.86   371.7 1084.87   391.5 1086.52   431.5 1094.16
   471.6 1107.91   481.6 1110.74   491.6 1111.68   521.6 1122.24   551.7 1129.82
   581.7 1141.47   591.7 1142.51   601.7 1145.97   651.8 1168.36   671.8 1178.32
#Mann= 3 , 0 , 0
       0      .1       0   272.4    .045       0   292.4     .08       0
Bank Sta=272.4,292.4
XS Rating Curve= 0 ,0
Exp/Cntr=0.3,0.1

Type RM Length L Ch R = 1 ,9289.6  ,219.9,229.9,239.9
XS GIS Cut Line= 4
     1699239.993      202714.635     1699036.447      202868.209
     1699044.979       203066.88     1699003.539        203339.9
#Sta/Elev= 30
     9.8 1214.49    19.6 1207.35    29.4 1202.79    68.6 1186.41    88.3 1179.87
    98.1 1175.17   107.9 1169.17   137.3 1156.54   176.5 1137.23   186.3 1130.33
   196.1 1122.15   225.6 1103.02   235.4 1097.95     255 1089.91   284.8 1082.21
   304.6 1075.91   314.6  1074.5   324.6 1074.65   404.1 1077.43   443.9 1084.48
   453.8 1084.73   503.1  1094.1   542.6 1111.26   552.5 1112.34     582 1122.79
   621.5  1133.6   641.2 1140.83   651.1 1143.76   660.9 1145.31     730 1177.99
#Mann= 3 , 0 , 0
       0      .1       0   304.6    .045       0   324.6     .08       0
Bank Sta=304.6,324.6
XS Rating Curve= 0 ,0
Exp/Cntr=0.3,0.1

Type RM Length L Ch R = 1 ,9059.7  ,223.4,221,218.6
XS GIS Cut Line= 4
     1698779.272      202583.001     1698870.685      202809.705
     1698770.741      203018.126     1698717.112      203304.553
#Sta/Elev= 30
     9.8 1206.66    39.1  1190.5    48.9 1189.81    58.7    1185   156.4 1127.98
   166.2 1125.89     176 1122.81   215.1 1102.65   244.4  1089.8   264.5 1083.07
   284.6 1080.47   324.8 1070.54   334.9 1068.89     345 1068.22     355 1068.14
     365 1068.45   425.3 1070.68   485.6  1071.3   505.7 1072.76   515.8  1076.9
   525.8 1083.75     566 1113.98   576.1 1120.54   596.2 1131.56   606.2 1131.69
   646.4 1153.08   696.7 1183.74   706.7 1185.38   716.7 1190.04     767 1224.31
#Mann= 3 , 0 , 0
       0      .1       0     345    .045       0     365     .08       0
Bank Sta=345,365
XS Rating Curve= 0 ,0
Exp/Cntr=0.3,0.1

Type RM Length L Ch R = 1 ,8838.7  ,241,238.8,236.5
XS GIS Cut Line= 4
      1698665.92       202584.22     1698636.668      202774.359
     1698586.696      202921.838     1698537.942      203233.861
#Sta/Elev= 30
    10.1  1206.7    20.3 1199.48    40.5 1192.21      81 1164.53   121.5 1139.76
   131.6 1135.72   141.8 1133.58   192.4  1104.6   231.3 1080.53     241 1079.53
   250.8 1073.95   260.5 1067.35     270 1064.09     280 1063.79     290 1064.67
   328.6  1067.5     358 1068.47   367.8 1069.53   417.2 1079.77     427 1082.65
   436.9 1086.43   456.7 1090.82     506  1111.9   545.5 1129.96   555.3  1130.3
   594.8 1148.32   634.3 1165.52   644.2 1169.46     654 1170.96   663.9 1173.54
#Mann= 3 , 0 , 0
       0      .1       0     270    .045       0     290     .08       0
Bank Sta=270,290
XS Rating Curve= 0 ,0
Exp/Cntr=0.3,0.1

Type RM Length L Ch R = 1 ,8599.9  ,157.3,150.6,143.8
XS GIS Cut Line= 4
     1698431.903      202550.092     1698395.338      202724.386
     1698361.211      202880.397     1698327.083       203129.04
#Sta/Elev= 30
     9.9 1195.93    19.8 1183.04    29.7  1173.3    39.6 1165.77    49.5 1165.41
    59.4 1158.78    79.2 1144.75      89 1138.22   108.8 1126.17   138.5 1109.47
   158.3 1104.25   188.1 1088.19     218 1072.79     238 1060.98   247.9 1058.49
   257.9 1058.43   267.9 1059.23   287.9 1062.51   297.9 1062.95   337.8 1062.57
   357.9 1063.58   367.9 1066.35   448.2  1107.3   468.3 1112.61   498.4 1128.61
   518.5 1138.38   548.6 1153.91   558.6 1157.61   568.7 1159.32   588.8 1169.92
#Mann= 3 , 0 , 0
       0      .1       0   247.9    .045       0   267.9      .1       0
Bank Sta=247.9,267.9
XS Rating Curve= 0 ,0
Exp/Cntr=0.3,0.1

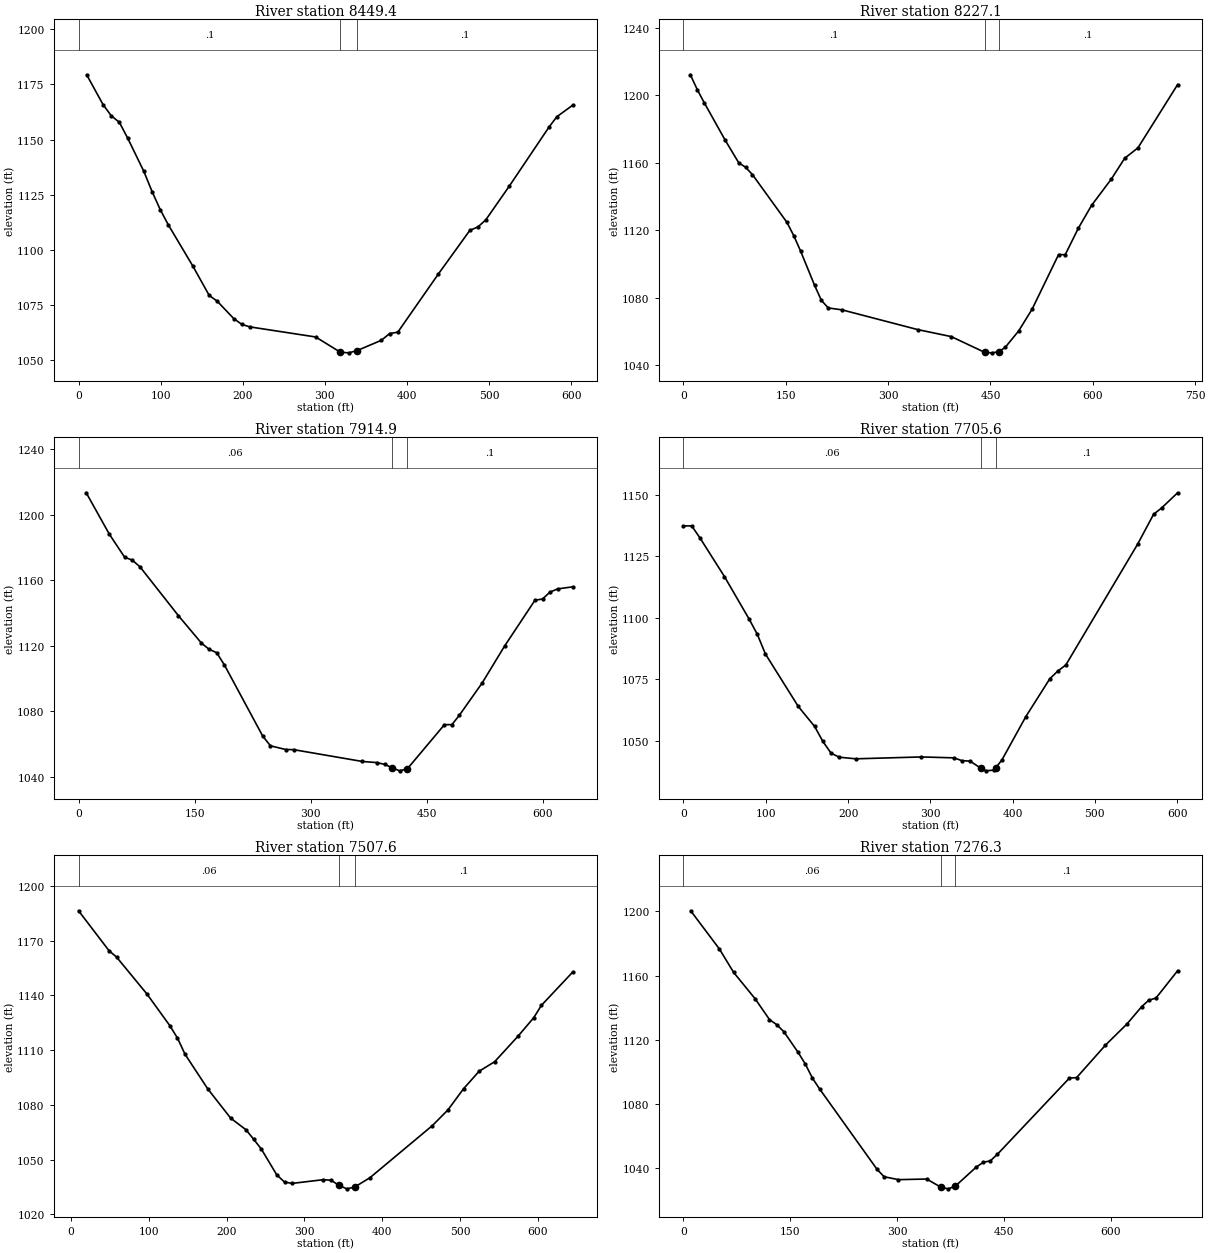
Type RM Length L Ch R = 1 ,8449.4  ,220.9,222.2,223.6
XS GIS Cut Line= 4
     1698359.992      202550.092      1698225.92      202735.356
     1698247.859      202924.276     1698269.798      203105.882
#Sta/Elev= 30
     9.9 1179.32    29.8 1165.83    39.8 1160.78    49.7 1157.78    59.7 1150.72
    79.5 1135.58    89.5 1126.46    99.4  1118.3   109.4  1111.3   139.2 1092.68
   159.1 1079.41     169 1076.75   188.9 1068.94   198.9 1066.26   208.8 1065.14
   288.7 1060.59   318.8 1053.69   328.8  1053.4   338.8 1054.35   368.8 1059.09
   378.8 1062.12   388.8 1062.76   438.1 1089.06   476.6 1108.89   486.3 1110.39
   495.9 1113.59   524.8 1129.02   572.9 1155.61   582.5 1160.33   601.8 1165.54
#Mann= 3 , 0 , 0
       0      .1       0   318.8    .045       0   338.8      .1       0
Bank Sta=318.8,338.8
XS Rating Curve= 0 ,0
Exp/Cntr=0.3,0.1

Type RM Length L Ch R = 1 ,8227.1  ,311.8,312.2,312.5
XS GIS Cut Line= 4
     1697835.892      202470.868     1698015.061      202728.043
     1698023.593      202925.494     1698027.249      203138.791
#Sta/Elev= 30
    10.1 1212.14    20.2 1203.34    30.3 1195.67    60.7 1173.69    80.9 1160.04
      91 1157.33   101.1 1152.99   151.7 1124.66   161.8 1116.68   171.9 1107.47
   192.1 1087.45   202.2 1078.42   212.3 1073.97   232.5 1072.83   343.1 1061.17
   392.5    1057   441.8 1047.62   451.8 1047.37   461.8 1047.98   471.5 1050.54
   491.3 1060.31   511.1 1073.26   549.9  1105.6   559.6 1105.52   578.9 1121.27
   598.3 1134.79   627.4 1150.47   646.8 1162.67   666.2 1168.83   724.4 1206.34
#Mann= 3 , 0 , 0
       0      .1       0   441.8    .045       0   461.8      .1       0
Bank Sta=441.8,461.8
XS Rating Curve= 0 ,0
Exp/Cntr=0.3,0.1

Type RM Length L Ch R = 1 ,7914.9  ,209,209.4,209.8
XS GIS Cut Line= 4
      1697774.95      202467.211     1697710.351      202808.486
     1697714.008      202943.777     1697765.199      203091.256
#Sta/Elev= 30
     9.9 1213.38    39.7 1188.17    59.5 1174.09    69.5 1172.24    79.4 1168.19
     129 1138.42   158.8 1121.67   168.7 1117.86   178.6 1115.77   188.6 1108.24
   238.2 1064.78   248.1 1058.94   267.9 1056.67   277.9 1056.61   366.7  1049.4
     386 1048.69   395.7 1047.61     405 1045.65     415 1043.67     425 1044.89
     473 1071.85   482.7 1071.88   492.4 1077.68   521.7 1097.26     551 1120.02
     590 1147.78   599.8 1148.56   609.5 1152.79   619.3  1154.7   638.8 1155.98
#Mann= 3 , 0 , 0
       0     .06       0     405    .045       0     425      .1       0
Bank Sta=405,425
XS Rating Curve= 0 ,0
Exp/Cntr=0.3,0.1

Type RM Length L Ch R = 1 ,7705.6  ,213.3,198,182.6
XS GIS Cut Line= 4
     1697248.412      202721.948     1697521.628      202904.948
     1697522.997      203021.289     1697607.553       203151.52
#Sta/Elev= 30
       0 1137.28      10 1137.28    19.9 1132.46    49.8 1116.71    79.7 1099.49
    89.7 1093.29    99.6 1085.27   139.5    1064   159.4 1055.87   169.4 1049.79
   179.4 1045.02   189.3 1043.41   209.3 1042.75     289 1043.51   328.8 1043.14
   338.5 1041.98   348.2 1041.83  361.36 1038.93   367.6 1037.87   377.3 1038.18
   379.2 1039.01     387  1042.3   416.1 1059.92   445.2 1075.25   454.9 1078.38
   464.6 1080.82   551.9 1129.87   571.3 1141.99   581.1 1144.58   600.5 1150.72
#Mann= 3 , 0 , 0
       0     .06       0  361.36    .045       0   379.2      .1       0
Bank Sta=361.36,379.2
XS Rating Curve= 0 ,0
Exp/Cntr=0.3,0.1

Type RM Length L Ch R = 1 ,7507.6  ,228,231.3,234.6
XS GIS Cut Line= 4
     1697080.212      202754.857     1697253.287      202913.306
      1697386.14      203048.597      1697554.34      203191.201
#Sta/Elev= 30
     9.8 1186.42    48.9 1164.57    58.7 1161.01    97.8 1140.74   127.1 1123.44
   136.9 1116.65   146.7 1107.72     176  1088.7   205.3 1072.75   224.9  1066.4
   234.7 1061.26   244.6 1055.86   264.6 1041.61   274.6 1037.69   284.5    1037
   324.5 1039.04   334.4 1038.71   344.4 1035.95   354.4 1034.01   364.4 1034.93
   384.3 1040.13   464.4 1068.65   484.4 1077.24   504.5 1088.85   524.5 1098.45
   544.5 1103.69   574.6  1117.7   594.7  1127.8   604.7 1134.64   644.8 1152.82
#Mann= 3 , 0 , 0
     9.8     .06       0   344.4    .045       0   364.4      .1       0
#XS Ineff= 2 , 0
       0     324                       0
Permanent Ineff=
       F       F
Bank Sta=344.4,364.4
XS Rating Curve= 0 ,0
Exp/Cntr=0.3,0.1

Type RM Length L Ch R = 1 ,7276.3  ,285,287.4,289.9
XS GIS Cut Line= 4
     1696919.325       202887.71     1697131.403      203102.226
     1697216.722       203224.11     1697304.478      203450.814
#Sta/Elev= 30
    10.1 1200.36    50.3 1176.62    70.4 1161.97   100.6 1145.52   120.7 1132.59
   130.7 1129.47   140.8 1125.09   160.9 1112.14   170.9 1104.97     181 1096.08
     191 1089.41   271.5  1039.4   281.5  1034.7   301.7 1032.88   341.3 1033.27
   361.1 1028.21   371.1 1027.16   381.1 1028.67   410.8 1040.68   420.7 1043.68
   430.6 1044.59   440.5 1048.66   541.6 1096.15   551.7 1096.43   592.2 1116.66
   622.6 1129.95   642.9 1140.58     653 1144.65   663.1 1145.99   693.5 1163.03
#Mann= 3 , 0 , 0
       0     .06       0   361.1    .045       0   381.1      .1       0
Bank Sta=361.1,381.1
XS Rating Curve= 0 ,0
Exp/Cntr=0.3,0.1