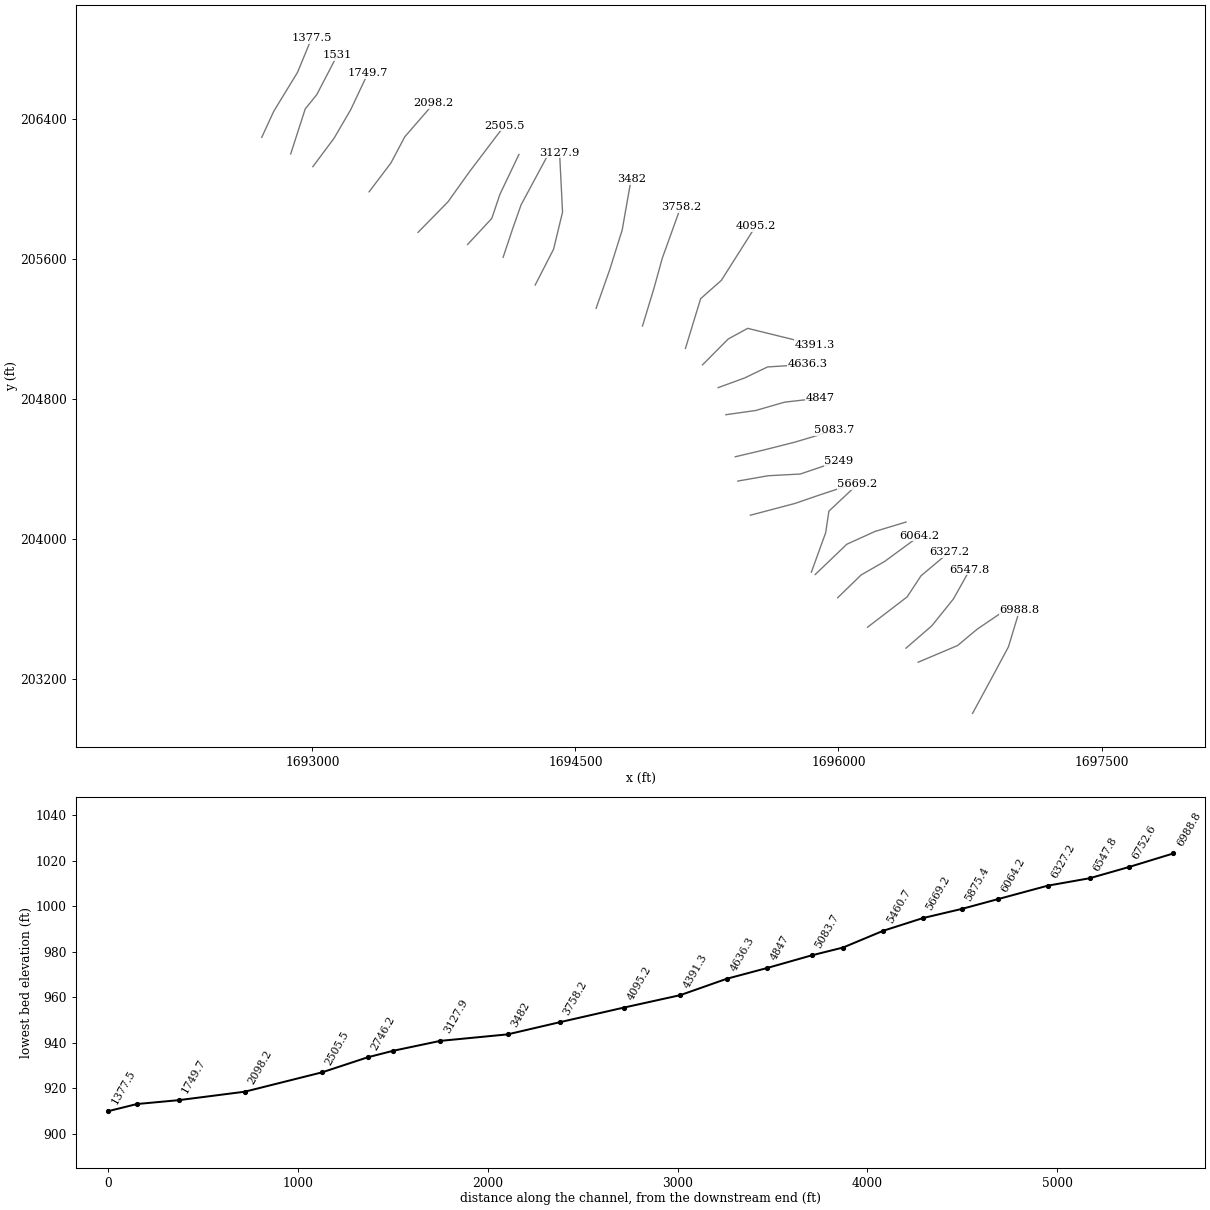
HEC-RAS study sprngfrk.prj: sprngfrk

--- sprngfrk.g01 (geometry) --- (continued)

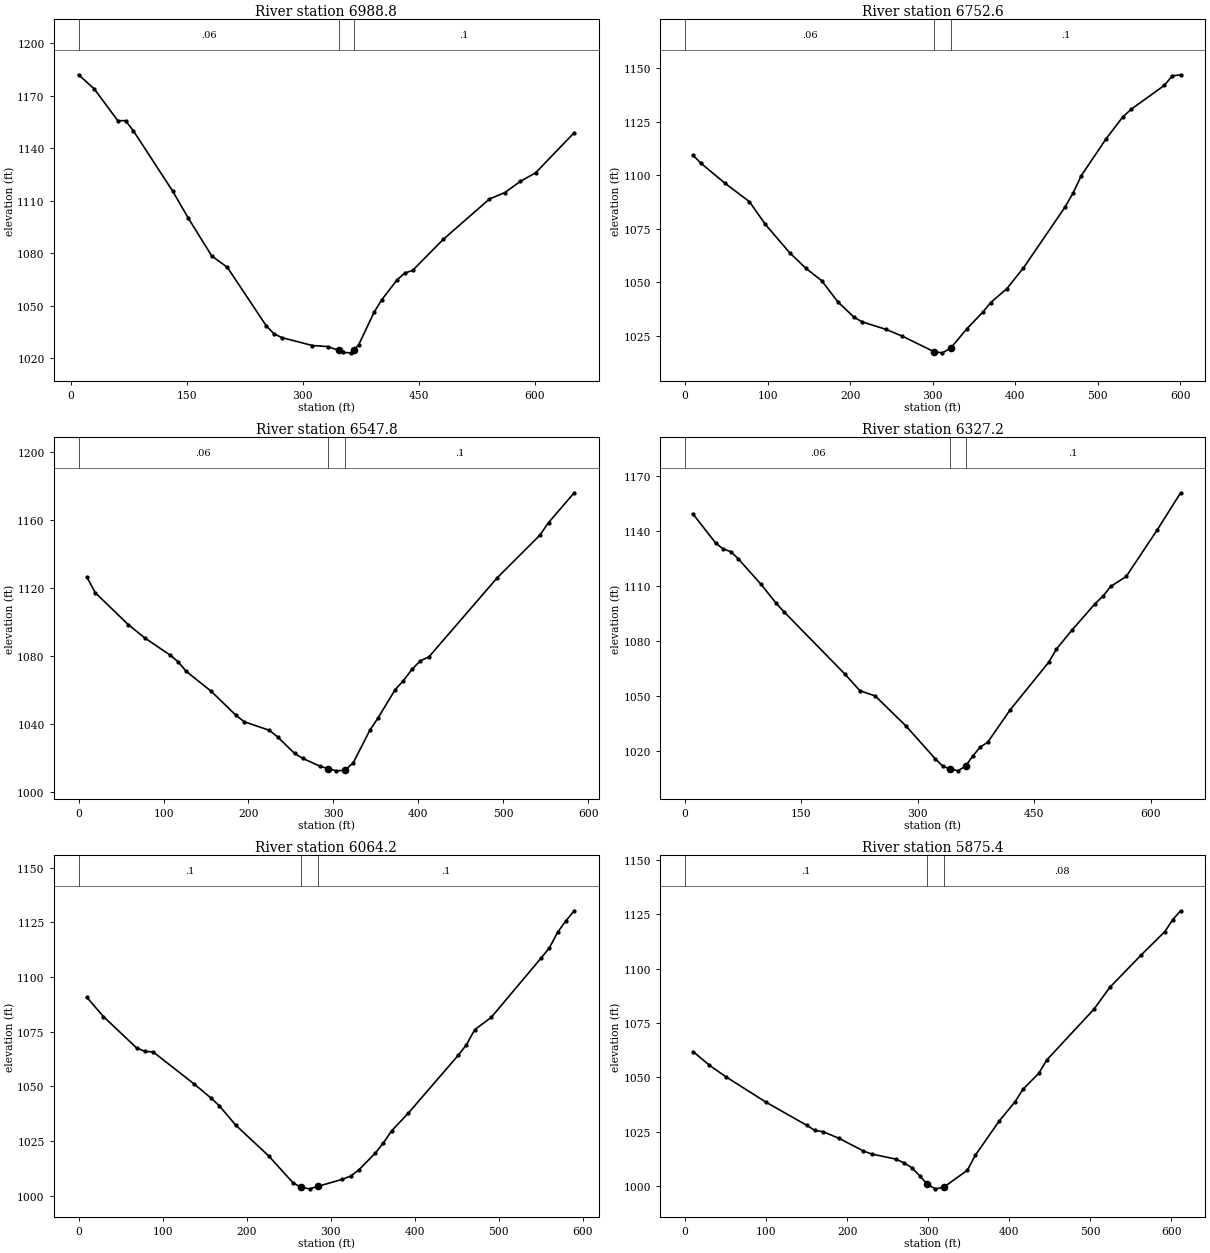
Type RM Length L Ch R = 1 ,6988.8  ,243.9,236.2,228.5
XS GIS Cut Line= 4
     1696764.533      203002.281     1696875.447      203207.046
     1696969.298      203382.559     1697032.677      203592.199
#Sta/Elev= 30
    10.1 1181.97    30.4 1173.84    60.7 1155.78    70.9 1155.72      81 1149.89
   131.6  1115.6   151.9 1100.09   182.2 1078.53   202.5 1071.91   252.8 1038.51
   262.7    1034   272.7 1031.86   312.5  1027.3   332.4 1026.71  346.32  1024.5
   352.3 1023.33   362.2 1023.13  366.08 1024.88   372.2 1027.69   392.1 1046.22
     402 1053.41     422 1064.88   431.9 1068.71   441.9 1070.18   481.7 1087.98
   541.4 1111.02   561.3 1114.68   581.2 1121.06   601.1 1125.99   650.9 1148.89
#Mann= 3 , 0 , 0
    10.1     .06       0  346.32    .045       0  366.08      .1       0
Bank Sta=346.32,366.08
XS Rating Curve= 0 ,0
Exp/Cntr=0.3,0.1

Type RM Length L Ch R = 1 ,6752.6  ,200.8,204.8,208.7
XS GIS Cut Line= 4
     1696454.948      203294.802     1696679.214      203389.872
     1696791.347      203483.722     1696965.641       203601.95
#Sta/Elev= 30
     9.7 1109.26    19.5 1105.49    48.7 1096.15    77.9 1087.66    97.4 1077.01
   126.7 1063.81   146.2 1056.61   165.6 1050.74   185.1 1040.89   204.6 1033.77
   214.4 1031.58   243.6 1028.03   263.1 1024.91   301.8 1017.59   311.8 1017.11
   321.8 1019.32   341.1 1028.22   360.6 1036.06   370.3 1040.58   389.8 1047.04
   409.9 1056.71     460 1084.94     470 1091.61   480.1 1099.85   510.2 1117.05
   530.2 1127.14   540.2  1130.7   580.4 1141.87   590.4 1146.38   600.4 1146.87
#Mann= 3 , 0 , 0
       0     .06       0   301.8    .045       0   321.8      .1       0
Bank Sta=301.8,321.8
XS Rating Curve= 0 ,0
Exp/Cntr=0.3,0.1

Type RM Length L Ch R = 1 ,6547.8  ,218.7,220.6,222.5
XS GIS Cut Line= 4
     1696385.049      203374.866     1696532.393      203502.708
     1696655.902      203656.553     1696749.075      203823.398
#Sta/Elev= 30
     9.8 1126.25    19.5 1117.13    58.5 1098.31      78 1090.45   107.3 1080.52
     117 1076.55   126.8 1070.75   156.1  1059.1   185.3 1044.89   195.1 1041.12
   224.7 1036.09   234.5 1032.13   254.3 1022.47   264.1 1019.53   283.9 1015.01
   293.6 1013.54   303.6 1012.24   313.6 1012.61   323.3 1016.92     343  1036.2
   352.9 1043.64   372.6 1059.99   382.5 1065.41   392.4 1071.91   402.4 1077.04
   412.5 1079.35   492.9 1125.91   543.2 1151.05   553.3 1158.39   583.5 1175.95
#Mann= 3 , 0 , 0
       0     .06       0   293.6    .045       0   313.6      .1       0
Bank Sta=293.6,313.6
XS Rating Curve= 0 ,0
Exp/Cntr=0.3,0.1

Type RM Length L Ch R = 1 ,6327.2  ,272.5,263,253.6
XS GIS Cut Line= 4
     1696166.083      203494.692     1696391.568      203667.767
     1696470.793      203788.432     1696631.679      203923.723
#Sta/Elev= 30
     9.8 1149.67    39.2 1133.71      49 1130.36    58.8 1128.93    68.6 1124.93
      98 1110.96   117.6 1100.56   127.4 1096.03   205.8 1061.99   225.4 1052.79
     245 1049.96   284.3 1033.71   322.7 1015.47   332.4 1011.47   341.6 1010.04
   351.6 1008.98   361.6 1011.56   370.9 1017.14   380.5 1021.96   390.1 1024.61
     419 1042.32   468.6 1068.32   478.6 1075.55   498.7 1085.94   528.7 1100.52
   538.7 1104.51   548.7 1109.87   568.7 1115.33   608.8 1140.91   638.8 1161.09
#Mann= 3 , 0 , 0
       0     .06       0   341.6    .045       0   361.6      .1       0
Bank Sta=341.6,361.6
XS Rating Curve= 0 ,0
Exp/Cntr=0.3,0.1

Type RM Length L Ch R = 1 ,6064.2  ,190.7,188.8,186.9
XS GIS Cut Line= 4
     1695995.446      203662.892     1696129.518      203793.307
     1696264.809      203871.313      1696463.48      204017.574
#Sta/Elev= 30
     9.8  1090.7    29.5 1081.92    68.9 1067.57    78.8 1065.98    88.6 1065.74
   137.8 1050.97   157.5 1044.62   167.4 1041.12     187 1032.21   226.1 1018.18
   255.4 1005.75   264.9 1003.78   274.9 1003.06   284.9 1004.21   313.9 1007.41
   323.7 1008.89   333.4 1011.68   353.1 1019.37   362.9 1024.16   372.8  1029.7
   392.5 1037.72   451.8 1064.15   461.6 1068.99   471.5 1075.88   491.2 1081.55
   550.4 1108.63   560.3 1113.28   570.2 1120.47     580 1125.68   589.9 1130.32
#Mann= 3 , 0 , 0
       0      .1       0   264.9    .045       0   284.9      .1       0
Bank Sta=264.9,284.9
XS Rating Curve= 0 ,0
Exp/Cntr=0.3,0.1

Type RM Length L Ch R = 1 ,5875.4  ,185.9,206.2,226.4
XS GIS Cut Line= 4
     1695867.468      203795.745     1696047.856       203968.82
     1696208.742       204041.95     1696385.474      204095.579
#Sta/Elev= 30
      10 1061.87      30 1055.62      50  1050.4     100  1038.6     150 1028.04
     160 1025.68     170  1025.1     190 1022.01     220  1016.2     230 1014.83
   259.8 1012.48   269.6 1010.85   279.4 1008.57   289.3 1004.89   298.9 1000.83
   308.9   998.8   318.9  999.51   348.2 1007.31     358 1014.19   387.4 1029.91
   407.1 1038.82   416.9 1044.61   436.4 1051.91   446.2 1058.04   504.5 1081.41
   523.9 1091.38   562.8 1106.34     592  1117.1   601.7 1122.58   611.4 1126.63
#Mann= 3 , 0 , 0
       0      .1       0   298.9    .045       0   318.9     .08       0
Bank Sta=298.9,318.9
XS Rating Curve= 0 ,0
Exp/Cntr=0.3,0.1

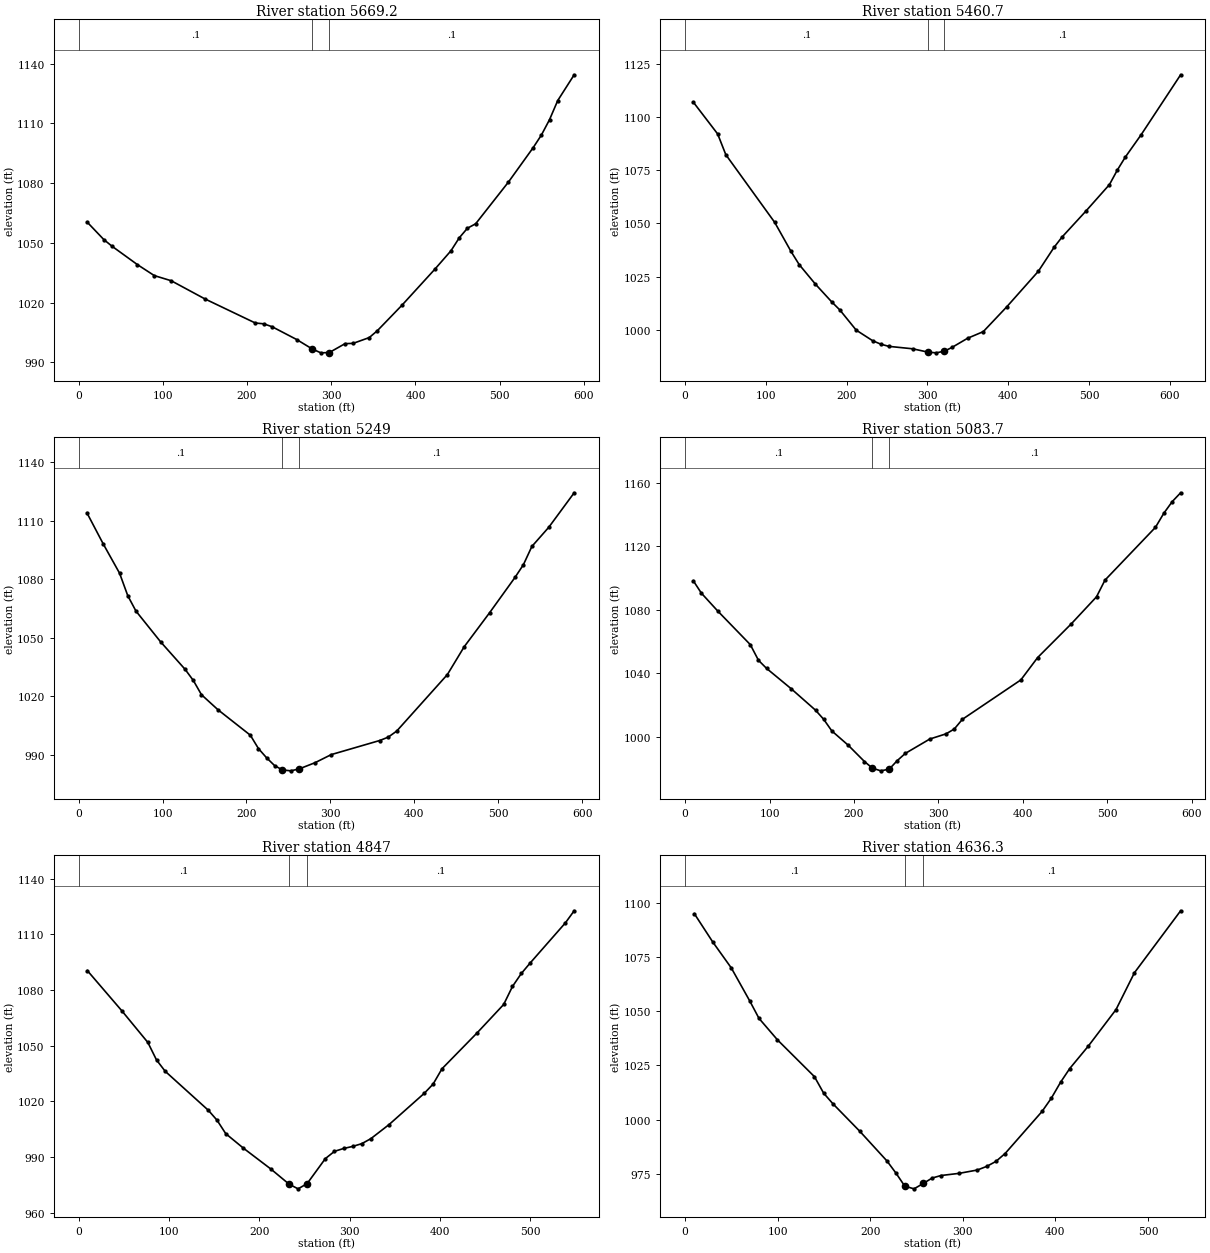
Type RM Length L Ch R = 1 ,5669.2  ,230.7,208.5,186.3
XS GIS Cut Line= 4
     1695845.529      203809.152     1695927.191      204034.637
     1695945.473       204157.74     1696108.798      204311.313
#Sta/Elev= 30
      10 1060.44      30 1051.57      40 1048.16    69.9 1039.01    89.9 1033.52
   109.9 1030.95   149.9 1021.84   209.8 1009.73   219.8 1009.32   229.8 1007.85
     259 1001.42   277.7  996.62   287.7  994.75   297.7   994.9   316.4  999.36
     326  999.51   345.1  1002.4   354.7 1005.84   383.8 1018.57   422.8 1036.62
   442.2    1046     452 1052.47   461.7  1057.3   471.5 1059.54   510.5 1080.52
   539.7 1097.69   549.5 1104.03   559.2 1111.78     569 1121.42   588.5 1134.34
#Mann= 3 , 0 , 0
       0      .1       0   277.7    .045       0   297.7      .1       0
Bank Sta=277.7,297.7
XS Rating Curve= 0 ,0
Exp/Cntr=0.3,0.1

Type RM Length L Ch R = 1 ,5460.7  ,217.5,211.7,205.9
XS GIS Cut Line= 4
      1695498.16      204134.582     1695751.678      204201.618
     1695889.407      204249.153     1696084.421      204313.751
#Sta/Elev= 30
    10.1 1106.98    40.3 1092.01    50.4 1082.27   110.9 1050.48   131.1 1036.83
   141.2 1030.65   161.4 1021.42   181.5 1013.12   191.6 1009.31   211.8  999.86
     232  994.92   242.1  993.28   252.1  992.24   281.7  991.09   300.8  989.51
   310.8  989.19   320.8  989.95   330.2   991.7   349.7  996.04   369.1  999.15
   398.2 1010.82   437.3 1027.52   456.8 1038.79   466.6 1043.58     496 1055.71
   525.3 1068.23   535.1 1075.08   544.9 1081.13   564.5 1091.63   613.4  1119.8
#Mann= 3 , 0 , 0
       0      .1       0   300.8    .045       0   320.8      .1       0
Bank Sta=300.8,320.8
XS Rating Curve= 0 ,0
Exp/Cntr=0.3,0.1

Type RM Length L Ch R = 1 ,5249    ,161.4,165.3,169.3
XS GIS Cut Line= 4
     1695426.248      204329.596     1695599.323      204360.067
     1695782.149      204369.818      1696001.54      204444.167
#Sta/Elev= 30
     9.8 1114.14    29.3 1098.15    48.8 1083.12    58.6 1071.56    68.3 1063.73
    97.6    1048   126.9 1033.84   136.7 1028.14   146.4 1020.84     166 1013.16
   204.6  1000.1   214.3  993.23   223.9  988.55   233.6  984.49   242.8   982.3
   252.8  981.83   262.8  982.82   281.7     986     301  990.15   358.8  997.38
   368.9   999.1     379  1002.2   439.4 1031.17   459.5 1045.47   489.8 1062.92
     520 1080.98     530 1087.49   540.1 1096.86   560.3 1106.71   590.5 1124.36
#Mann= 3 , 0 , 0
       0      .1       0   242.8    .045       0   262.8      .1       0
Bank Sta=242.8,262.8
XS Rating Curve= 0 ,0
Exp/Cntr=0.3,0.1

Type RM Length L Ch R = 1 ,5083.7  ,236,236.7,237.4
XS GIS Cut Line= 4
     1695411.622      204468.544      1695571.29      204506.328
     1695749.241      204551.425     1695978.382      204619.679
#Sta/Elev= 30
     9.7 1098.19    19.3 1090.38    38.6 1079.15    77.2 1057.94    86.9 1048.06
    96.5 1042.95   125.5 1030.19   154.4 1016.64   164.1 1010.87   173.7 1003.56
   193.1  994.56   212.4  984.25   221.7  980.11   231.7   978.4   241.7  979.47
     251  984.75   260.7  989.38   289.7  998.44     309 1001.72   318.7 1004.76
   328.3 1010.87   397.5  1035.7   417.4  1049.8   457.2 1071.03   487.1 1088.08
   497.1 1098.58   556.9 1131.88   566.8 1140.76   576.8 1148.12   586.7 1153.65
#Mann= 3 , 0 , 0
       0      .1       0   221.7    .045       0   241.7      .1       0
Bank Sta=221.7,241.7
XS Rating Curve= 0 ,0
Exp/Cntr=0.3,0.1

Type RM Length L Ch R = 1 ,4847    ,207.4,210.7,214.1
XS GIS Cut Line= 4
     1695357.994      204708.655     1695528.631      204733.032
     1695693.174      204780.566      1695896.72      204803.724
#Sta/Elev= 30
     9.6 1090.46    47.9 1068.73    76.6 1051.73    86.2 1042.28    95.8 1036.18
   143.6 1015.13   153.2  1009.8   162.8 1002.57   182.4  994.72   212.7  983.51
   232.9  975.34   242.9   972.8   252.9   975.6   273.1   989.1   283.2  993.02
   293.3  994.56   303.3  995.66   313.4  997.15   323.5  999.86   343.6 1007.44
   382.7 1024.35   392.4  1029.3   402.2 1037.53   441.2 1056.94   470.5  1072.2
   480.2 1081.89     490 1088.88   499.7 1094.49   538.7 1116.13   548.5 1122.69
#Mann= 3 , 0 , 0
       0      .1       0   232.9    .045       0   252.9      .1       0
Bank Sta=232.9,252.9
XS Rating Curve= 0 ,0
Exp/Cntr=0.3,0.1

Type RM Length L Ch R = 1 ,4636.3  ,243.9,245,246
XS GIS Cut Line= 4
     1695314.115      204863.447     1695464.033      204918.295
     1695595.667      204981.675     1695824.809      204996.301
#Sta/Elev= 30
      10 1094.84    29.9  1081.8    49.9 1069.87    69.8 1054.69    79.8 1046.65
    99.8 1036.73   139.7  1019.8   149.7 1012.17   159.6 1007.34   188.9  994.55
   218.1  980.94   227.8  975.36   237.3  969.37   247.3  968.12   257.3   970.6
   266.8  973.08   276.5  974.26     296  975.25   315.7  976.79   325.7  978.44
   335.7  980.73   345.7  984.39   385.6 1003.77   395.6 1009.86   405.6 1017.21
   415.5 1023.53   435.5 1033.83   465.5 1050.69   485.4 1067.66   535.3 1096.19
#Mann= 3 , 0 , 0
       0      .1       0   237.3    .045       0   257.3      .1       0
Bank Sta=237.3,257.3
XS Rating Curve= 0 ,0
Exp/Cntr=0.3,0.1

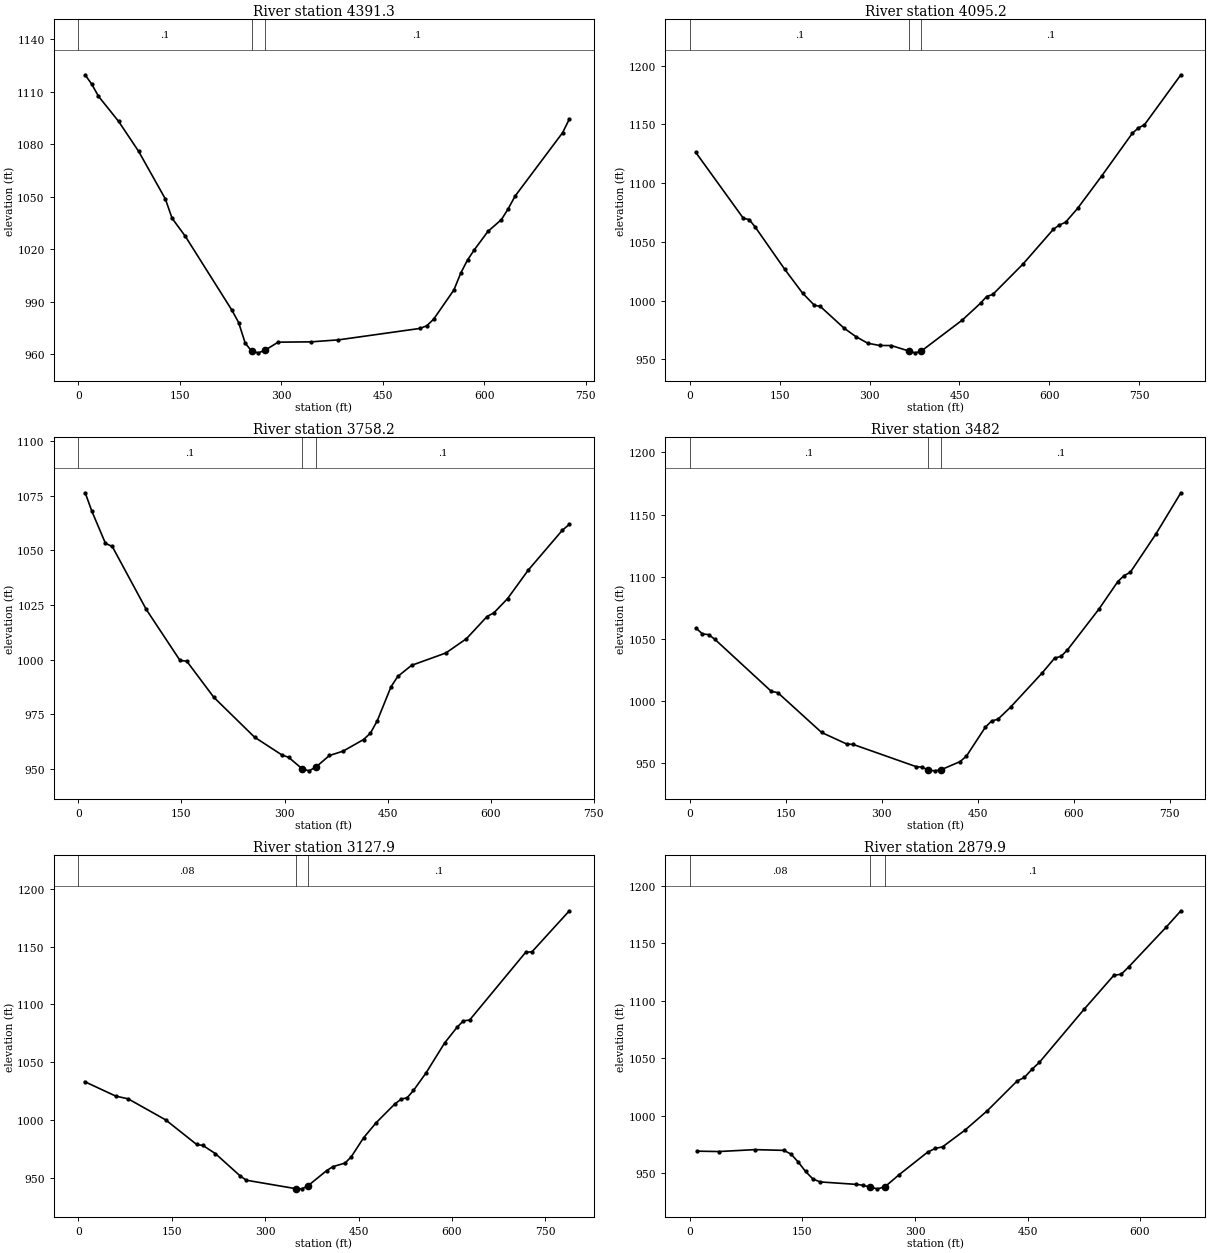
Type RM Length L Ch R = 1 ,4391.3  ,291.6,296.1,300.7
XS GIS Cut Line= 4
      1695225.14      204993.863     1695371.401      205141.342
     1695482.315      205202.284     1695862.592      205108.434
#Sta/Elev= 30
     9.9  1119.7    19.8 1114.28    29.7 1107.43    59.3 1093.17      89 1076.01
   128.6 1048.76   138.5 1037.78   158.3 1027.36   227.2  985.13   236.9  978.23
   246.6  966.51   256.1  961.92   266.1  960.93   276.1  962.45   295.3  967.02
   344.3  967.21   384.5  968.34     505  974.87     515  976.37   525.1  980.08
   555.2  996.84   565.3 1006.44   575.3 1013.92   585.3 1019.71   605.4 1030.22
   625.5 1037.02   635.6 1043.28   645.6  1050.4   715.9 1086.63   725.9 1094.44
#Mann= 3 , 0 , 0
       0      .1       0   256.1    .045       0   276.1      .1       0
Bank Sta=256.1,276.1
XS Rating Curve= 0 ,0
Exp/Cntr=0.3,0.1

Type RM Length L Ch R = 1 ,4095.2  ,325.2,336.9,348.7
XS GIS Cut Line= 4
     1695127.633      205087.713     1695214.171      205371.703
     1695332.398      205476.523     1695527.412      205784.889
#Sta/Elev= 30
     9.9 1126.03    89.1 1070.09      99 1068.89   108.9 1062.66   158.3 1026.61
     188 1006.38   207.8  995.98   217.7  994.98   257.3  976.53   277.1   969.3
   296.9  963.69   316.6  961.76   336.4  961.69   365.9  956.97   375.9  955.49
   385.9  956.83   454.9  983.45   485.3  997.77   495.4 1003.43   505.6 1005.16
   556.2 1031.11   606.9 1060.69     617 1064.35   627.2 1066.65   647.4 1078.52
     688 1106.37   738.7 1142.39   748.8 1146.94   758.9 1149.61   819.7 1192.17
#Mann= 3 , 0 , 0
       0      .1       0   365.9    .045       0   385.9      .1       0
Bank Sta=365.9,385.9
XS Rating Curve= 0 ,0
Exp/Cntr=0.3,0.1

Type RM Length L Ch R = 1 ,3758.2  ,276.9,276.3,275.6
XS GIS Cut Line= 4
     1694882.647      205215.691     1694948.464      205432.645
     1694995.999      205604.501     1695100.819      205895.803
#Sta/Elev= 30
     9.9 1076.31    19.7 1067.77    39.4 1053.16    49.3 1051.74    98.6 1023.02
   147.9  999.59   157.7  999.27   197.1  982.74   256.4  964.49   296.1  956.38
     306  955.27   325.7  950.01   335.7  949.09   345.7  950.83   365.4  956.11
   385.2  958.09     415   963.4     425  966.31     435  971.98     455  987.56
   464.9   992.3   484.9  997.35   534.9 1003.02   564.8 1009.55   594.8 1019.69
   604.8 1021.39   624.7  1027.9   654.7  1040.9   704.6 1059.25   714.6 1061.84
#Mann= 3 , 0 , 0
       0      .1       0   325.7    .045       0   345.7      .1       0
Bank Sta=325.7,345.7
XS Rating Curve= 0 ,0
Exp/Cntr=0.3,0.1

Type RM Length L Ch R = 1 ,3482    ,352.8,354.1,355.3
XS GIS Cut Line= 4
     1694618.159      205316.855     1694696.164      205538.683
     1694766.857      205764.169     1694818.048      206055.471
#Sta/Elev= 30
     9.8 1058.46    19.6 1053.92    29.4 1053.32    39.2 1049.47   127.4  1007.6
   137.2 1006.71   205.8  974.59     245  965.32   254.8  965.02   353.3  947.14
   363.1  946.67   372.8  944.24   382.8  943.72   392.8  944.67   422.2  951.15
   432.1  955.58   461.6  978.77   471.5  983.85   481.3  985.25     501  994.93
   550.3 1022.42     570 1034.45   579.9 1035.83   589.8 1040.92   639.1 1073.84
   668.6 1095.98   678.5 1100.82   688.3 1103.56   727.8 1133.99   767.2 1167.49
#Mann= 3 , 0 , 0
       0      .1       0   372.8    .045       0   392.8      .1       0
Bank Sta=372.8,392.8
XS Rating Curve= 0 ,0
Exp/Cntr=0.3,0.1

Type RM Length L Ch R = 1 ,3127.9  ,250,248,246
XS GIS Cut Line= 4
      1694270.79      205449.708      1694375.61      205654.473
     1694426.801      205866.551     1694409.737      206206.607
#Sta/Elev= 30
      10 1033.41      60 1020.92      80 1018.54     140 1000.45     190  979.16
     200  978.31     220  971.31   259.8  952.05   269.7  948.32     349  941.04
     359  940.87     369  943.58   398.6  956.52   408.5  959.94   428.4  963.14
   438.3  968.53   458.2  984.97   478.2  997.89   508.3  1014.1   518.3 1018.18
   528.3 1019.61   538.3  1025.8   558.4 1040.87   588.4 1066.84   608.4 1080.39
   618.4 1085.84   628.5 1086.58   718.6  1145.1   728.6 1145.44   788.7 1180.88
#Mann= 3 , 0 , 0
       0     .08       0     349    .045       0     369      .1       0
Bank Sta=349,369
XS Rating Curve= 0 ,0
Exp/Cntr=0.3,0.1

Type RM Length L Ch R = 1 ,2879.9  ,133.4,133.8,134.1
XS GIS Cut Line= 4
     1694087.964      205608.157     1694142.812      205772.701
     1694190.346      205907.991     1694350.014      206205.388
#Sta/Elev= 30
     9.6  969.25    38.5  968.93    86.7  970.59   125.3  969.94   134.9  966.63
   144.5  959.71   154.2   951.6   163.8  945.19   173.4  942.55   221.2  940.43
   230.8  939.65   239.9  938.05   249.9  936.53   259.9  938.26   278.6  948.69
   316.8  968.35   326.8   971.6   336.7  972.97   366.5  987.44   396.3 1004.31
     436 1030.11   445.9 1033.33   455.8 1040.32   465.8 1046.36   525.3 1092.41
     565 1121.95     575    1123   584.9 1129.31   634.5 1163.62   654.4 1178.06
#Mann= 3 , 0 , 0
       0     .08       0   239.9    .045       0   259.9      .1       0
Bank Sta=239.9,259.9
XS Rating Curve= 0 ,0
Exp/Cntr=0.3,0.1

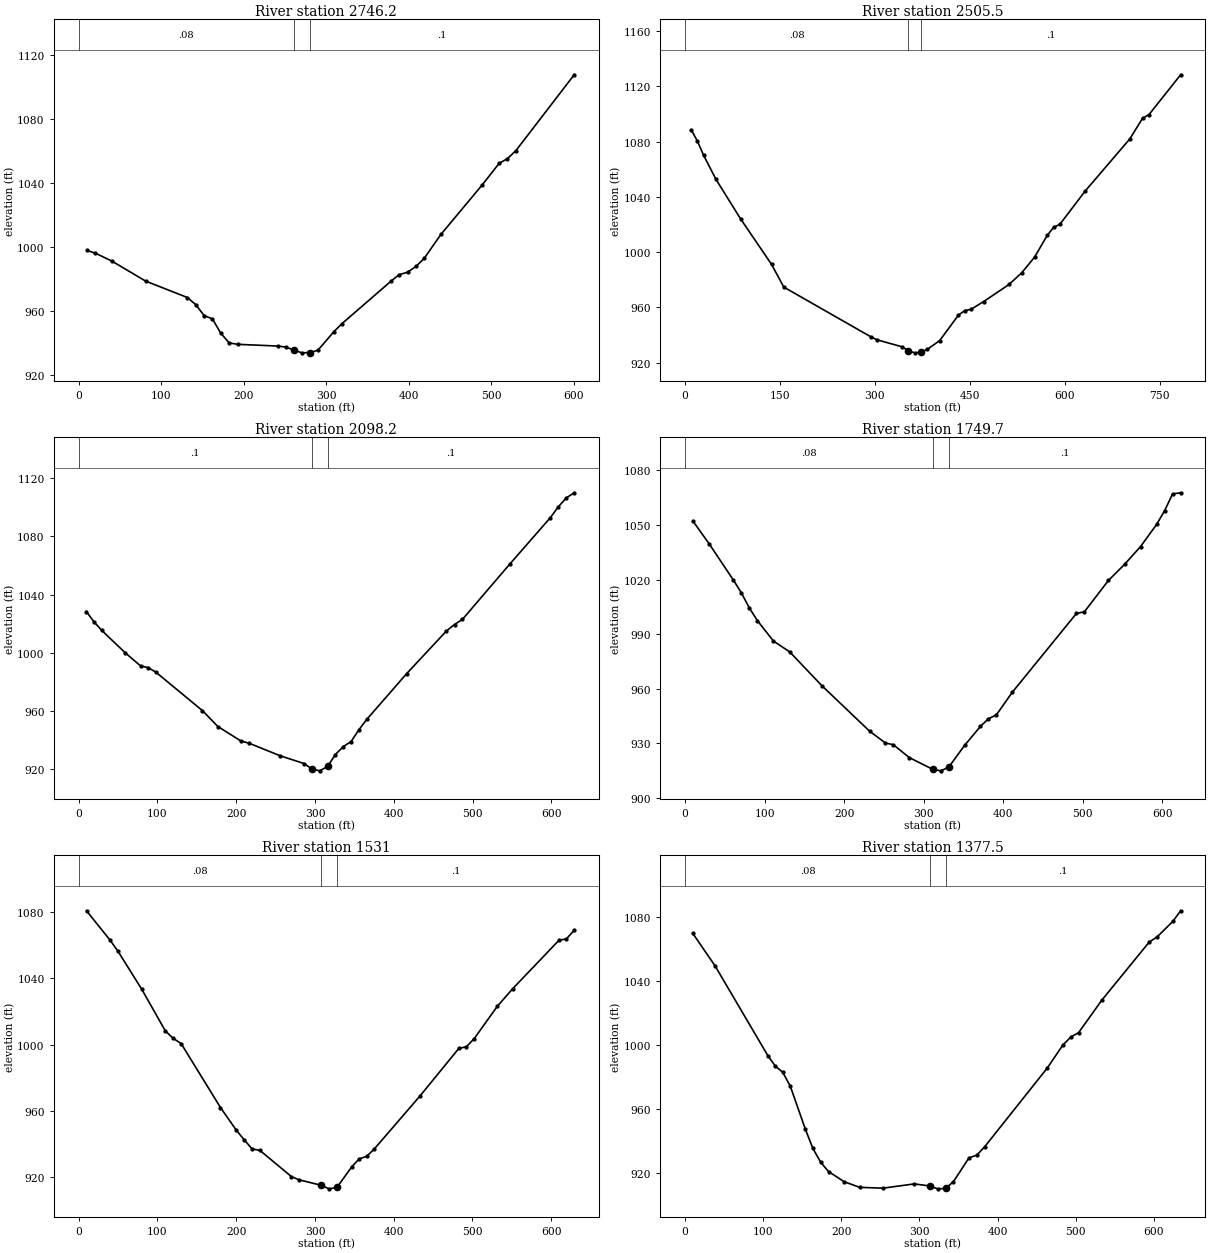
Type RM Length L Ch R = 1 ,2746.2  ,246.7,240.7,234.7
XS GIS Cut Line= 4
     1693885.618      205681.653     1694023.347      205830.351
     1694069.663       205968.08     1694178.139      206196.002
#Sta/Elev= 30
    10.1  997.77    20.3  996.06    40.5  991.03    81.1   978.6   131.7  968.31
   141.9  963.86     152  957.03   162.1  954.93   172.3  945.93   182.4  939.91
   192.5  939.02   241.4  937.92   251.1  937.28   260.5  935.47   270.5  933.68
   280.5  933.88   289.9  935.31   309.2  946.88   318.9  951.88   378.3  978.45
   388.4  982.62   398.5  984.13   408.6  987.72   418.7  992.81   438.9 1007.77
   489.3 1038.98   509.5 1052.27   519.6 1055.26   529.7 1060.17   600.4  1107.7
#Mann= 3 , 0 , 0
       0     .08       0   260.5    .045       0   280.5      .1       0
Bank Sta=260.5,280.5
XS Rating Curve= 0 ,0
Exp/Cntr=0.3,0.1

Type RM Length L Ch R = 1 ,2505.5  ,404.7,407.4,410
XS GIS Cut Line= 4
     1693602.867      205750.762     1693773.504      205925.055
     1693894.169      206094.474     1694094.058      206358.962
#Sta/Elev= 30
     9.8 1088.54    19.5 1080.34    29.3  1070.1    48.8 1052.73    87.8 1024.03
   136.6  991.19   156.1  974.65   293.4  938.74   303.3  936.53     343  931.44
   352.8  928.65   362.8  927.07   372.8  927.49   382.6  929.49   402.4  935.91
   432.1  954.35     442  957.62   451.9  958.56     472  964.21   512.2  976.61
   532.3   985.1   552.4  996.33   572.5 1012.11   582.5 1017.92   592.6 1020.22
   632.7 1044.36   703.1 1082.02   723.2 1096.93   733.2 1099.52   783.4 1128.44
#Mann= 3 , 0 , 0
       0     .08       0   352.8    .045       0   372.8      .1       0
Bank Sta=352.8,372.8
XS Rating Curve= 0 ,0
Exp/Cntr=0.3,0.1

Type RM Length L Ch R = 1 ,2098.2  ,349.3,348.5,347.7
XS GIS Cut Line= 4
     1693323.753      205982.341     1693448.074      206146.884
     1693527.299      206296.801     1693693.061      206488.159
#Sta/Elev= 30
     9.8 1028.29    19.6 1021.08    29.5 1015.23    58.9  999.97    78.6  990.83
    88.4  989.62    98.2  986.46   157.1  960.06   176.8  949.07   206.2  939.08
   216.2  937.63   256.1  928.89     286  923.62     296  919.92     306  918.57
     316  921.57   325.9  929.81   335.9  935.23   345.9  938.77   355.8  946.88
   365.8  954.03   416.3  985.48   466.9  1014.9   477.1 1019.32   487.2 1022.89
   547.9 1061.34   598.6  1092.8   608.7 1100.23   618.8 1106.42     629 1110.05
#Mann= 3 , 0 , 0
       0      .1       0     296    .045       0     316      .1       0
Bank Sta=296,316
XS Rating Curve= 0 ,0
Exp/Cntr=0.3,0.1

Type RM Length L Ch R = 1 ,1749.7  ,221.7,218.7,215.7
XS GIS Cut Line= 4
     1693003.198      206126.164     1693123.863      206288.269
     1693218.933      206451.593     1693317.658      206661.233
#Sta/Elev= 30
    10.1 1051.98    30.3 1039.61    60.6 1019.78    70.7 1012.72    80.8  1004.3
    90.9  997.41   111.1  986.16   131.4  980.28   171.8   961.7   231.9  936.64
   251.8  930.14   261.8   929.2   281.7  922.15   311.4  915.65   321.4  914.85
   331.4  916.92   351.3  928.85   371.2   939.3   381.1  943.45   391.1  945.55
   411.2  958.03   491.8 1001.34   501.9 1002.31   532.1 1019.53   552.3 1028.33
   572.4 1038.12   592.6 1050.31   602.6  1057.8   612.7 1067.07   622.8  1067.7
#Mann= 3 , 0 , 0
       0     .08       0   311.4    .045       0   331.4      .1       0
Bank Sta=311.4,331.4
XS Rating Curve= 0 ,0
Exp/Cntr=0.3,0.1

Type RM Length L Ch R = 1 ,1531    ,150.9,153.5,156.1
XS GIS Cut Line= 4
     1692876.759      206198.914      1692959.64      206456.089
     1693025.457      206537.751     1693142.466      206763.236
#Sta/Elev= 30
      10 1080.57      40 1062.84      50 1056.17    80.1 1033.34   110.1 1008.24
   120.1 1003.73   130.1 1000.65   180.1  962.09   200.1  948.53   210.2  942.68
   220.2  937.22   230.2  936.28   270.2  920.52   279.7  918.64   307.9  915.31
   317.9  913.17   327.9  914.01   346.5  926.28     356  931.18   365.5  932.69
   375.1  937.04   433.7  969.26   482.6  997.66   492.3  998.76   502.1 1003.56
   531.4 1022.97     551 1033.62   609.6  1062.7   619.3 1063.71   629.1  1068.8
#Mann= 3 , 0 , 0
       0     .08       0   307.9    .045       0   327.9      .1       0
Bank Sta=307.9,327.9
XS Rating Curve= 0 ,0
Exp/Cntr=0.3,0.1

Type RM Length L Ch R = 1 ,1377.5  ,258,261.5,265
XS GIS Cut Line= 4
     1692711.778      206293.742     1692780.032       206442.44
     1692915.324      206664.269     1692995.767      206859.283
#Sta/Elev= 30
     9.6 1069.89    38.5 1049.27   105.9   993.3   115.5  986.73   125.1  982.84
   134.7  974.14     154  947.22   163.6  935.25   173.6  926.65   183.6  920.82
   203.6  914.47   223.6  910.92   253.6  910.44   293.5  913.09   313.5  911.76
   323.5     910   333.5  910.23   343.5  914.48   363.5  929.39   373.5  931.08
   383.5   936.3   463.6  985.49   483.7  999.95   493.8 1004.88   503.8 1007.68
   533.9 1028.21   594.2 1064.29   604.3 1067.51   624.4 1077.19   634.4 1083.83
#Mann= 3 , 0 , 0
       0     .08       0   313.5    .045       0   333.5      .1       0
Bank Sta=313.5,333.5
XS Rating Curve= 0 ,0
Exp/Cntr=0.3,0.1