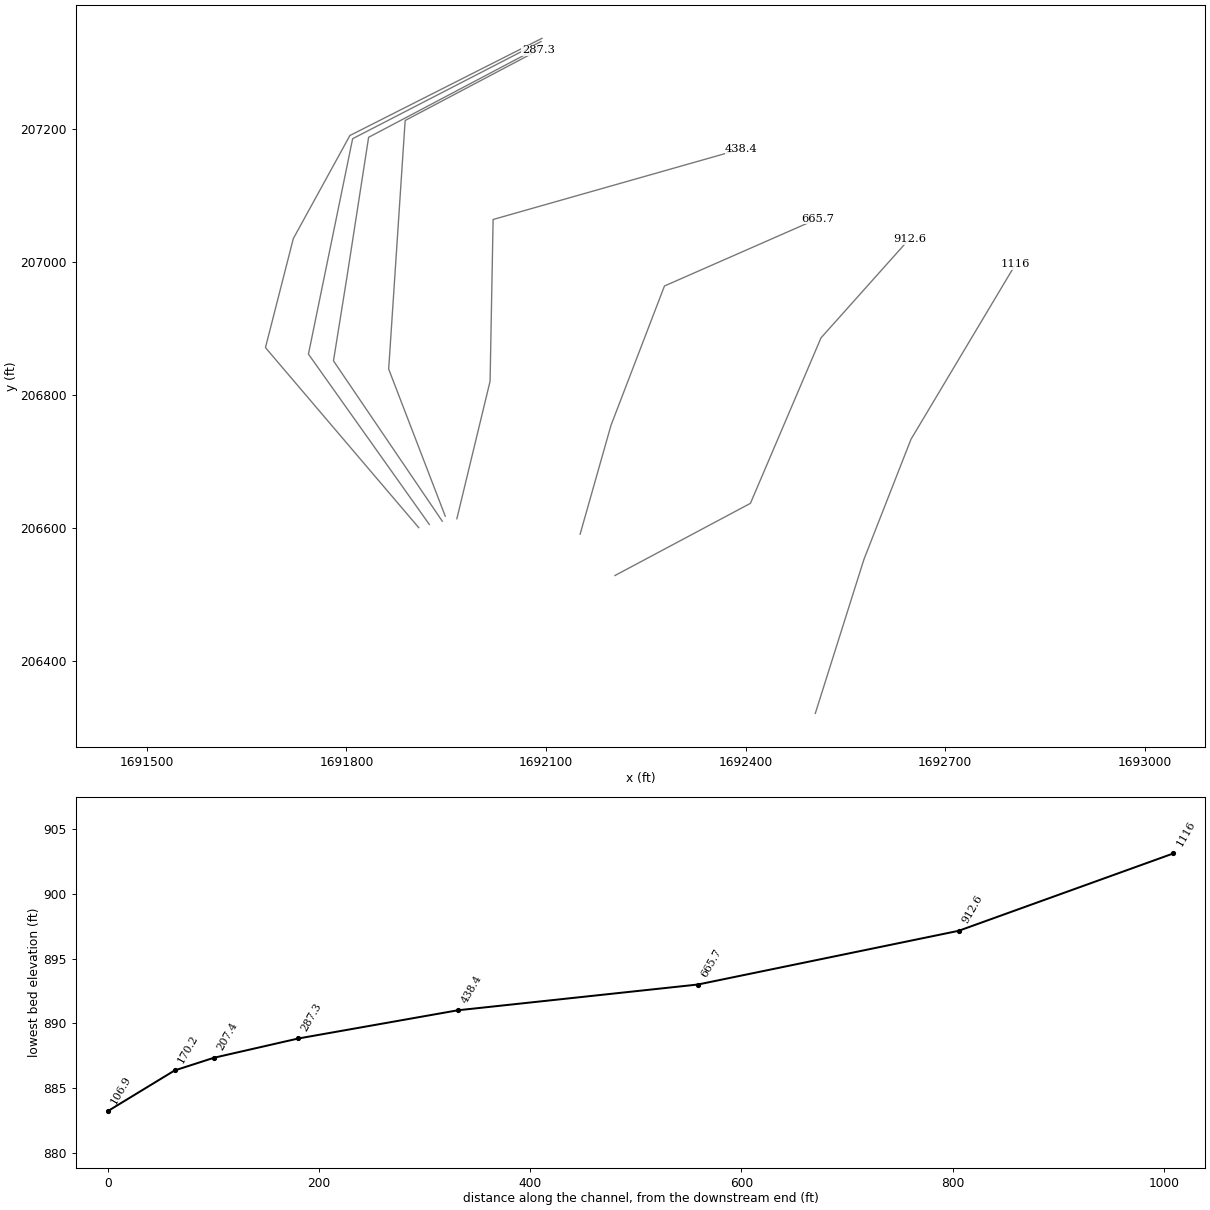
HEC-RAS study sprngfrk.prj: sprngfrk

--- sprngfrk.g01 (geometry) --- (continued)

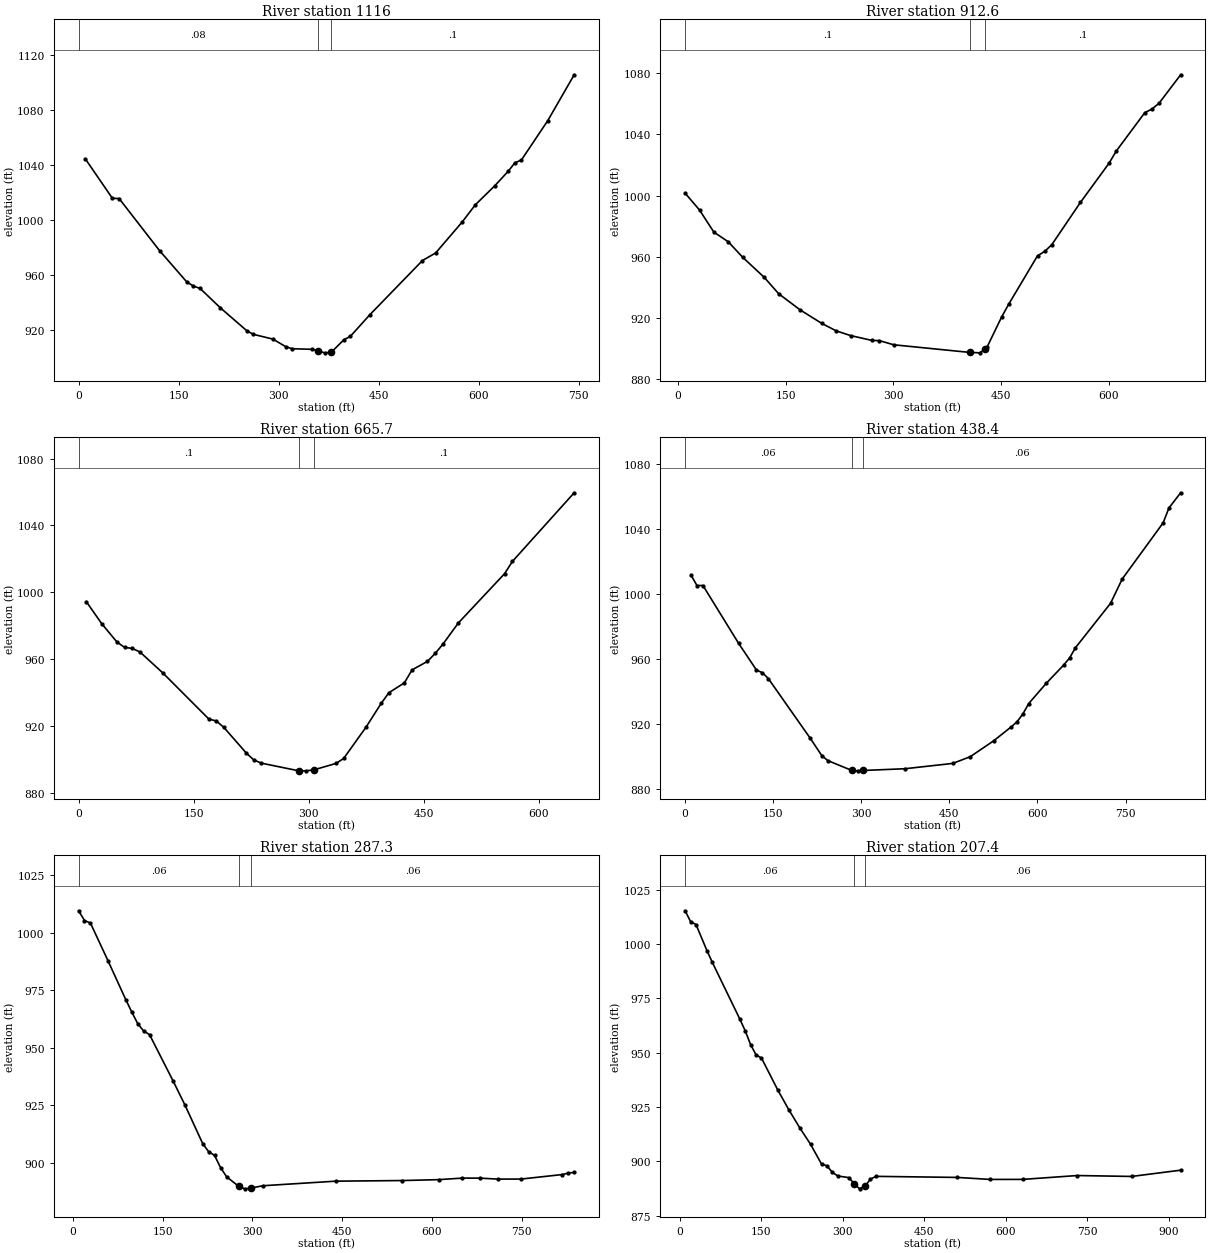
Type RM Length L Ch R = 1 ,1116    ,204.3,203.4,202.5
XS GIS Cut Line= 4
     1692504.693      206321.178     1692577.824      206552.757
     1692648.516      206733.145     1692805.746      206996.414
#Sta/Elev= 30
    10.1 1044.11    50.6 1015.48    60.7 1015.31   121.4  977.41   161.9  954.84
     172  951.69   182.1  949.97   212.5  935.88   252.5  919.08   262.2  916.55
   291.3  913.14   310.7  907.59   320.3  906.12   349.4   905.7   358.8  904.71
   368.8  903.13   378.8  903.47   397.8  912.64   407.5  915.09   436.6  930.75
   515.7  970.25   535.5  975.76   575.1  998.16   594.9 1010.73   624.5 1024.78
   644.3 1035.14   654.2 1041.24   664.1 1043.34   703.7 1072.02   743.2 1105.28
#Mann= 3 , 0 , 0
       0     .08       0   358.8    .045       0   378.8      .1       0
Bank Sta=358.8,378.8
XS Rating Curve= 0 ,0
Exp/Cntr=0.3,0.1

Type RM Length L Ch R = 1 ,912.6   ,246.1,246.9,247.7
XS GIS Cut Line= 4
      1692203.64       206528.38     1692407.186      206636.857
     1692513.225        206885.5     1692646.079      207034.198
#Sta/Elev= 30
      10 1001.55    30.1  990.52    50.1  976.06    70.2  969.74    90.3   959.6
   120.3  946.48   140.4  935.77   170.5  925.15   200.6  916.35   220.6   911.5
   240.7  908.42   270.7  905.23   280.7  905.15   300.7  902.41  406.54  897.43
   420.9  897.15  427.79  899.77   430.9  901.11   450.9  920.49   460.9  928.99
     501   960.6   510.9  963.42   520.9  967.86   560.8  995.51   600.7 1021.14
   610.6 1028.99   650.5  1054.2   660.5 1056.55   670.4 1060.37   700.4 1078.94
#Mann= 3 , 0 , 0
      10      .1       0  406.54    .045       0  427.79      .1       0
Bank Sta=406.54,427.79
XS Rating Curve= 0 ,0
Exp/Cntr=0.3,0.1

Type RM Length L Ch R = 1 ,665.7   ,220.3,227.3,234.2
XS GIS Cut Line= 4
      1692151.23      206590.541     1692197.546      206753.865
     1692277.989      206963.505      1692508.35      207064.669
#Sta/Elev= 30
      10  994.36      30  981.22    49.9   970.2    59.9  966.96    69.9  966.35
    79.9  964.21   109.8  951.64   169.8     924   179.5  922.87   189.3     919
   218.6  903.64   228.3  899.54   238.1  897.61   286.7  893.04   296.7     893
   306.7   893.6   335.7  897.47   345.5  900.44   374.8   919.3   394.3  933.39
   404.4   939.8   424.5  945.68   434.6  953.47   454.7   958.6   464.8  963.37
   474.8  968.88   494.9  981.58   555.3 1011.17   565.4 1018.47   645.9 1059.59
#Mann= 3 , 0 , 0
       0      .1       0   286.7    .045       0   306.7      .1       0
Bank Sta=286.7,306.7
XS Rating Curve= 0 ,0
Exp/Cntr=0.3,0.1

Type RM Length L Ch R = 1 ,438.4   ,152,151.1,150.2
XS GIS Cut Line= 4
     1691965.967      206613.699     1692015.893      206820.316
     1692020.463      207063.474     1692393.779      207169.489
#Sta/Elev= 30
    10.1 1011.56    20.2 1005.17    30.4 1005.19    91.1  969.57   121.5  953.13
   131.6  951.46   141.7  947.88   212.6  911.33   232.8  900.39     243  897.31
   283.6   891.3   293.6  891.01   303.6  891.23   374.7  892.32   455.8  895.59
   485.6  899.73   525.4   909.5   555.3  918.08   565.2  921.23   575.2  926.07
   585.1  932.47     615  944.95   644.8  956.25   654.8  960.61   664.7  966.86
   724.4   994.2   744.3 1009.18     814  1043.8   823.9 1052.97   843.8 1062.32
#Mann= 3 , 0 , 0
       0     .06       0   283.6    .045       0   303.6     .06       0
Bank Sta=283.6,303.6
XS Rating Curve= 0 ,0
Exp/Cntr=0.3,0.1

Type RM Length L Ch R = 1 ,287.3   ,81.8,79.9,78.1
XS GIS Cut Line= 4
     1691948.518      206617.586     1691863.502      206838.658
     1691888.269      207212.243     1692088.378      207317.889
#Sta/Elev= 30
     9.9 1009.51    19.7 1005.28    29.6 1004.19    59.2  987.69    88.8  970.85
    98.7  965.56   108.6  960.51   118.4  957.35   128.3  955.77   167.8  935.59
   187.5  925.19   217.1  908.47     227  904.96   236.9  903.33     247     898
   257.1  894.05   277.4  889.88   287.5  888.83   297.4  889.15   317.8  890.18
   439.2  892.16   550.5  892.43   611.3  892.82   650.6  893.49   680.1  893.48
   709.6  893.06     749  893.08   817.9  895.04   827.7  895.67   837.5  895.95
#Mann= 3 , 0 , 0
     9.9     .06       0   277.4    .045       0   297.4     .06       0
#XS Ineff= 2 , 0
       0     267             467       0
Permanent Ineff=
       F       F
Bank Sta=277.4,297.4
XS Rating Curve= 0 ,0
Exp/Cntr=0.3,0.1

Type RM Length L Ch R = 1 ,207.4   ,38,37.2,36.3
XS GIS Cut Line= 5
     1691944.028      206610.042     1691780.545      206850.998
     1691801.113      206979.205     1691833.336       207186.94
     1692090.435      207322.689
#Sta/Elev= 30
      10 1015.24    20.1 1010.26    30.1 1008.91    50.2  996.93    60.2  991.46
   110.4  965.59   120.5  960.11   130.5  953.72   140.6  948.96   150.6   947.5
   180.7  932.75   200.8  923.76   220.9  915.46     241  907.79   261.1  898.72
   271.1  897.92   281.1  894.89   291.2  893.24   311.2  892.51   321.1  889.78
   331.1  887.34   341.1  888.63   351.1  891.76   361.1  893.08   511.1  892.59
   571.2  891.67   631.2  891.68   731.5  893.46   831.8  893.04     922  895.92
#Mann= 3 , 0 , 0
      10     .06       0   321.1    .045       0   341.1     .06       0
#XS Ineff= 2 , 0
       0                     361       0
Permanent Ineff=
       F       F
Bank Sta=321.1,341.1
XS Rating Curve= 0 ,0
Exp/Cntr=0.3,0.1

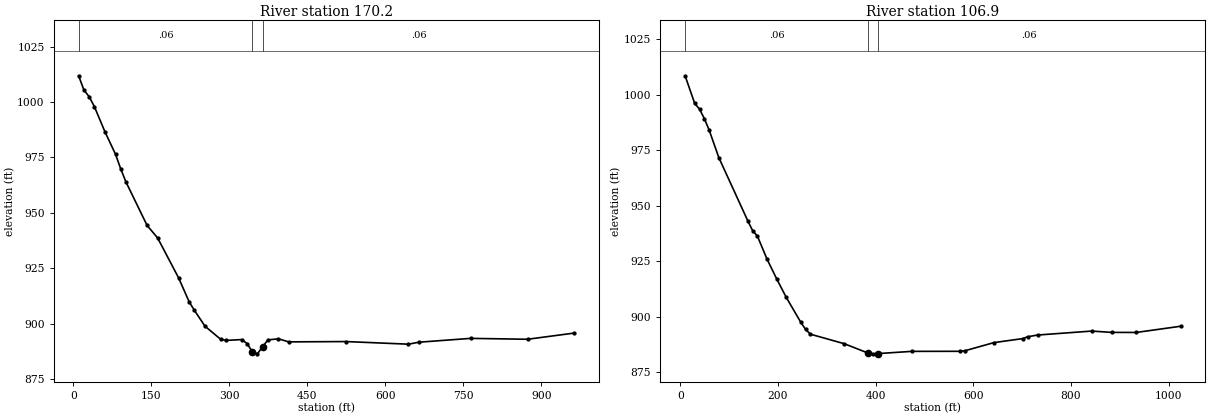
Type RM Length L Ch R = 1 ,170.2   ,64.3,63.4,62.4
XS GIS Cut Line= 4
     1691924.526      206605.167     1691742.919      206861.123
      1691809.34      207184.884     1692092.491      207330.916
#Sta/Elev= 30
    10.1 1011.86    20.2 1005.45    30.4 1002.42    40.5  997.87    60.7  986.58
      81  976.45    91.1   969.8   101.2  963.88   141.7  944.33     162  938.66
   202.5  920.56   222.7  909.79   232.8  905.96   253.1  898.82   283.5  892.86
   293.6  892.42   323.9   892.8   333.9  891.01   343.9  887.37   353.9  886.36
   363.9  889.58   373.9  892.63     394  893.16     414  891.76   524.2   891.9
   644.3  890.72   664.3  891.61   763.8  893.34   873.3  892.94   962.9  895.73
#Mann= 3 , 0 , 0
    10.1     .06       0   343.9    .045       0   363.9     .06       0
#XS Ineff= 2 , 0
       0                     394       0
Permanent Ineff=
       F       F
Bank Sta=343.9,363.9
XS Rating Curve= 0 ,0
Exp/Cntr=0.3,0.1

Type RM Length L Ch R = 1 ,106.9   ,103.4,106.9,110.3
XS GIS Cut Line= 5
     1691908.682      206600.292     1691678.321      206870.874
     1691720.172      207034.707     1691805.226      207189.683
     1692093.863      207335.715
#Sta/Elev= 30
     9.9 1008.47    29.6     996    39.5  993.42    49.4  989.14    59.2     984
      79   971.6   138.2  943.17   148.1  938.75   157.9  936.28   177.7  925.87
   197.4  917.01   217.2  908.59   246.8  897.44   256.6  894.24   266.5  892.06
   335.6  887.79   385.1  883.52   395.1  883.21   405.1  883.33   474.7  884.33
   573.6  884.35   583.4  884.63   642.3  888.27   701.2  890.07   711.3  890.89
   731.6  891.68   842.8  893.47   883.2  892.87   933.7  892.84  1024.7  895.64
#Mann= 3 , 0 , 0
     9.9     .06       0   385.1    .045       0   405.1     .06       0
#XS Ineff= 2 , 0
       0     375             464       0
Permanent Ineff=
       F       F
Bank Sta=385.1,405.1
XS Rating Curve= 0 ,0
Exp/Cntr=0.3,0.1
Stream Node=sprngfrk        ,Main            , 0 , 0 ,Upstream end
Stream Node=sprngfrk        ,Main            , 0 , 1 ,Downstream end

Chan Stop Cuts=-1
Use User Specified Reach Order=0